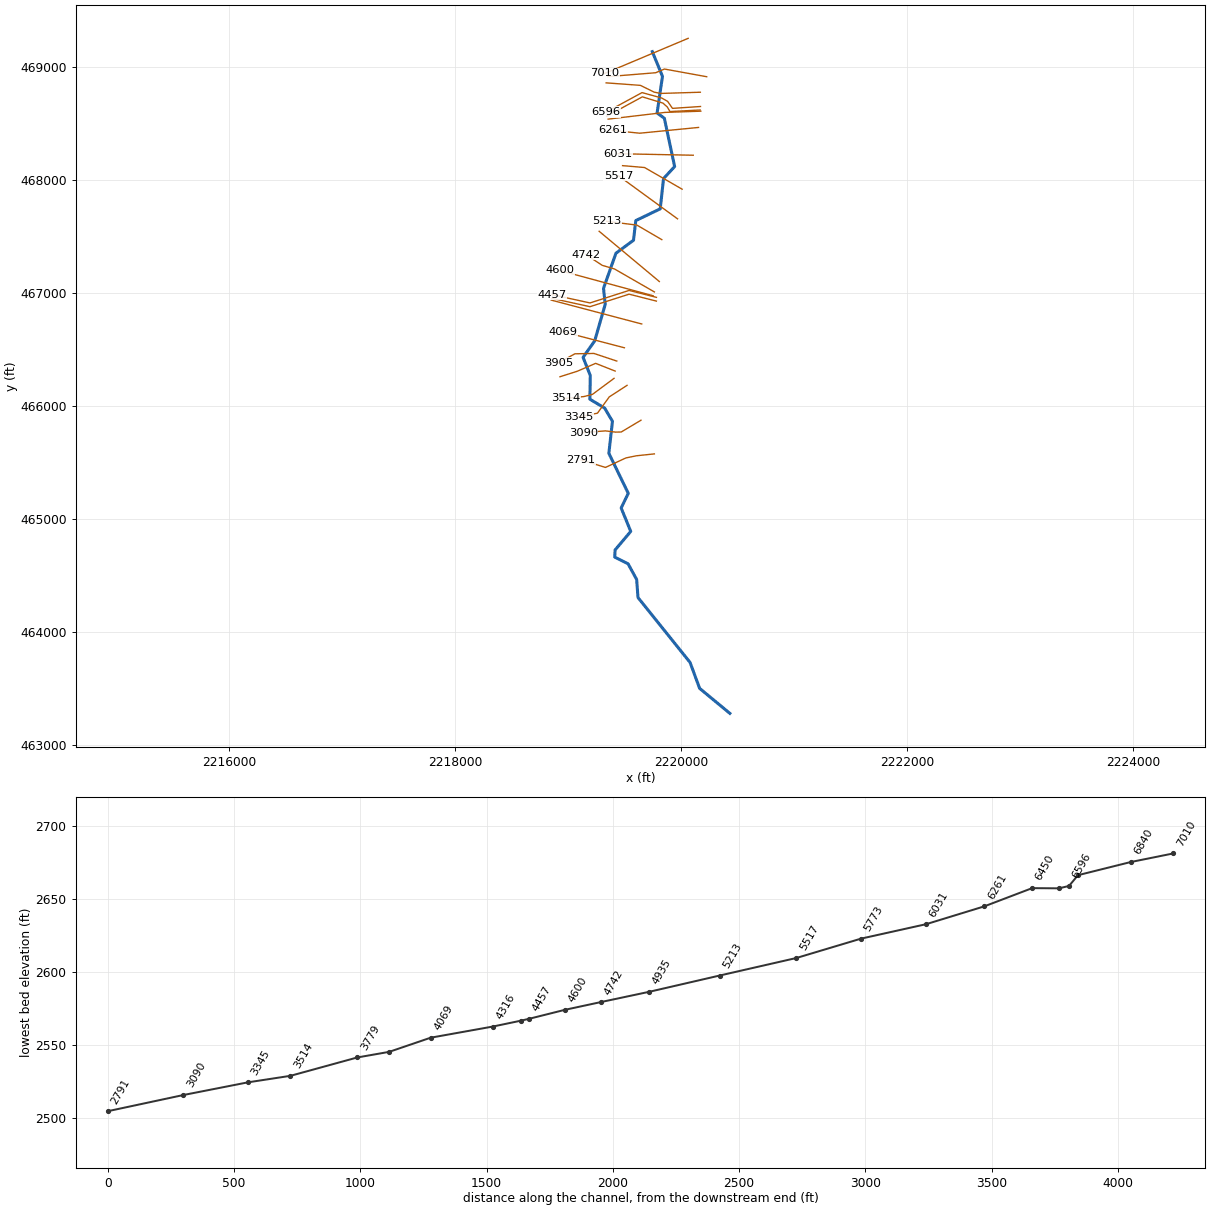
--- STONYCKT1.prj (project) ---

Proj Title=STONYCKT1
Current Plan=p01
Default Exp/Contr=0,0
English Units
Geom File=g01
Flow File=f01
Plan File=p01
Background Map Layer=Inundation Boundary (01pct Value_0)
BEGIN DESCRIPTION:
----------MODEL BY WOOD PLC 2021----------
Stream Name: Stony Creek Tributary 1
Flood Zone: Enhanced Approximate
Pocahontas County, WV
HEC-RAS Version: RAS 6.1
Vertical Datum: NAVD88
Projection: NAD 1983 StatePlane West Virginia S FIPS 4702 (US Feet)
Terrain: 1-meter LIDAR (FEMA Region III 3DEP collected 2016-2018)
Land Use: 2019 NLCD
Hydrologic Method:
WV SIR2010-5033 regression equations
Model Notes:
Normal depth tie in to Stony Creek
END DESCRIPTION:
DSS File=dss
DSS Export Rating Curves= 0
DSS Export Rating Curve Sorted= 0
DSS Export Volume Flow Curves= 0
DXF OffsetX= 0
DXF OffsetY= 0
DXF ScaleX= 0
DXF ScaleY= 0

--- STONYCKT1.p01 (plan) ---

Plan Title=Floodplain
Program Version=6.10
Short Identifier=Floodplain
Geom File=g01
Flow File=f01
Subcritical Flow
K Sum by GR= 0
Std Step Tol= 0.01
Critical Tol= 0.01
Num of Std Step Trials= 20
Max Error Tol= 0.3
Flow Tol Ratio= 0.001
Split Flow NTrial= 30
Split Flow Tol= 0.02
Split Flow Ratio= 0.02
Log Output Level= 0
Friction Slope Method= 1
Unsteady Friction Slope Method= 2
Unsteady Bridges Friction Slope Method= 1
Parabolic Critical Depth
Global Vel Dist= 0 , 0 , 0
Global Log Level= 0
CheckData=True
Encroach Param=-1 ,0,0, 0
Computation Interval=0.1SEC
Output Interval=1SEC
Instantaneous Interval=Max Profile
Mapping Interval=1HOUR
Computation Time Step Use Courant=        0
Computation Time Step Use Time Series=    0
Computation Time Step Count To Double=0
Computation Time Step Max Doubling=0
Computation Time Step Max Halving=0
Computation Time Step Residence Courant=0
Run HTab= 0
Run UNet= 0
Run Sediment= 0
Run PostProcess= 0
Run WQNet= 0
Run RASMapper= 0
UNET Theta= 0
UNET Theta Warmup= 0
UNET ZTol= 0
UNET ZSATol= 0
UNET MxIter= 0
UNET Max Iter WO Improvement= 0
UNET MaxInSteps= 0
UNET DtIC= 0
UNET DtMin= 0
UNET MaxCRTS= 0
UNET WFStab= 0
UNET SFStab= 0
UNET WFX= 1
UNET SFX= 1
UNET Gravity=32.174
UNET 1D Methodology=Finite Difference
UNET DSS MLevel= 1
UNET Pardiso=0
UNET DZMax Abort= 0
UNET Use Existing IB Tables= 0
UNET Froude Reduction=False
UNET Froude Limit= 0
UNET Froude Power= 0
UNET D1 Cores= 0
UNET WindReference=Eulerian
UNET WindDragFormulation=Hsu (1988)
UNET D2 Coriolis=0
UNET D2 Cores= 0
UNET D2 Theta= 1
UNET D2 Theta Warmup= 1
UNET D2 Z Tol= 0.01
UNET D2 Volume Tol= 0.01
UNET D2 Max Iterations= 20
UNET D2 Equation= 0
UNET D2 RampUpFraction=0.1
UNET D2 TimeSlices= 1
UNET D2 Turbulence Formulation=Non-Conservative (original)
UNET D2 Eddy Viscosity=0.3
UNET D2 Transverse Eddy Viscosity=0.1
UNET D2 Smagorinsky Mixing=0
UNET D2 BCVolumeCheck=0
UNET D2 Cores=0
UNET D2 SolverType=PARDISO (Direct)
UNET D2 Minimum Iterations= 2147483647
UNET D2 Maximum Iterations= 2147483647
UNET D2 Restart Number= 10
UNET D2 Relaxation Coeff=1.3
UNET D2 SOR Precondition Iterations= 10
UNET D2 ILUT Maximum Fill= 8
UNET D2 ILUT Tolerance=1E-08
UNET D1D2 MaxIter= 0
UNET D1D2 ZTol=0.01
UNET D1D2 QTol=0.1
UNET D1D2 MinQTol=1
DSS File=dss
Write IC File= 0
Write IC File at Fixed DateTime=0
Write IC File at Sim End=0
Echo Input=False
Echo Parameters=False
Echo Output=False
Write Detailed= 0
HDF Write Warmup=0
HDF Write Time Slices=0
HDF Flush=0
HDF Compression= 1
HDF Chunk Size= 1
HDF Spatial Parts= 1
HDF Use Max Rows=0
HDF Fixed Rows= 1
Calibration Method= 0
Calibration Iterations= 20
Calibration Max Change=0.05
Calibration Tolerance=0.2
Calibration Maximum=1.5
Calibration Minimum=0.5
Calibration Optimization Method= 1
WQ AD Non Conservative
WQ ULTIMATE=-1
WQ Max Comp Step=1HOUR
WQ Output Interval=15MIN
WQ Output Selected Increments= 0
WQ Output face flow=0
WQ Output face velocity=0
WQ Output face area=0
WQ Output face dispersion=0
WQ Output cell volume=0
WQ Output cell surface area=0
WQ Output cell continuity=0
WQ Output cumulative cell continuity=0
WQ Output face conc=0
WQ Output face dconc_dx=0
WQ Output face courant=0
WQ Output face peclet=0
WQ Output face adv mass=0
WQ Output face disp mass=0
WQ Output cell mass=0
WQ Output cell source sink temp=0
WQ Output nsm pathways=0
WQ Output nsm derived pathways=0
WQ Create Restart=0
WQ Fixed Restart=0
WQ System Summary=0
WQ Write To DSS=0
Sorting and Armoring Iterations= 10
XS Update Threshold= 0.02
Bed Roughness Predictor= 0
Hydraulics Update Threshold= 0.02
Energy Slope Method= 1
Volume Change Method= 1
Sediment Retention Method= 0
Sediment TS Multiplier= 1
Warm Up Method= 0
XS Weighting Method= 0
Number of US Weighted Cross Sections= 1
Number of DS Weighted Cross Sections= 1
Upstream XS Weight=0
Main XS Weight=1
Downstream XS Weight=0
Number of DS XS's Weighted with US Boundary= 1
Upstream Boundary Weight= 1
Weight of XSs Associated with US Boundary= 0
Number of US XS's Weighted with DS Boundary= 1
Downstream Boundary Weight= 0.5
Weight of XSs Associated with DS Boundary= 0.5
Percentile Method= 0
Sediment Output Level= 3
Mass or Volume Output= 0
Output Increment Type= 1
Profile and TS Output Increment= 1
Transport Output Increment 1
XS Output Flag= 0
XS Output Increment= 10
Read HDF5 Sediment Hotstart= 0
Sediment Hotstart Type= 0
Write Gradation File= 0
Read Gradation Hotstart= 0
Write HDF5 File= 1
Write Binary Output= 1
Write DSS Sediment File= 0
DSS Sediment Output Type= 1
SV Curve= 0
Specific Gage Flag= 0
Subcell Erosion Methods= 0
Subcell Deposition Methods= 0
Advection Scheme= 1
Matrix Solver= 0
Implicit Weighting Factor= 1
Maximum Outer Loop Convergence Iterations= 5
Convergence Maximum Absolute= 0.001
Convergence RMSE= 0.0001
Grain Fractions Max Abs Error= 0.001
Max Subgrid Regions= 1
Max Subgrid Length Scale= 3.402823E+38
Initial Layer Thickness= 3.402823E+38
Min Layer Thickness= 3.402823E+38
Max Layer Thickness= 3.402823E+38
Number of Layers= 5

--- STONYCKT1.f01 (steady flow) ---

Flow Title=Flow
Program Version=6.10
Number of Profiles= 6
Profile Names=01pct,10pct,04pct,02pct,0_2pct,01plus
River Rch & RM=STONYCKT1,Main            ,7010
     589     312     414     499     823     871
River Rch & RM=STONYCKT1,Main            ,3905
     656     349     462     556     914     970
Boundary for River Rch & Prof#=STONYCKT1,Main            , 1
Up Type= 0
Dn Type= 3
Dn Slope=0.05363
Boundary for River Rch & Prof#=STONYCKT1,Main            , 2
Up Type= 0
Dn Type= 3
Dn Slope=0.05363
Boundary for River Rch & Prof#=STONYCKT1,Main            , 3
Up Type= 0
Dn Type= 3
Dn Slope=0.05363
Boundary for River Rch & Prof#=STONYCKT1,Main            , 4
Up Type= 0
Dn Type= 3
Dn Slope=0.05363
Boundary for River Rch & Prof#=STONYCKT1,Main            , 5
Up Type= 0
Dn Type= 3
Dn Slope=0.05363
Boundary for River Rch & Prof#=STONYCKT1,Main            , 6
Up Type= 0
Dn Type= 3
Dn Slope=0.05363
DSS Import GetInterval= 0
DSS Import GetPeak= 0
DSS Import FillOption= 0

--- STONYCKT1.g01 (geometry) ---

Geom Title=Geometry
Program Version=6.10

River Reach=STONYCKT1       ,Main
Reach XY= 30
2219742.08890794469135.0881563522219831.94856621468916.525917771
2219784.23049149468592.4861095612219848.59918408468545.439141552
     2219939.449      468117.8052219841.41402298468012.100196084
2219811.98700815467743.977128663     2219595.671      467640.017
2219575.56274411467466.126833776     2219420.116      467351.026
     2219310.215      467040.638     2219325.098      466898.469
     2219232.079      466575.326     2219129.341      466429.759
     2219193.227      466268.6252219189.33032339466059.301711338
     2219319.872      465981.112     2219389.285       465863.57
 2219357.3575386465580.5392351162219529.22978013 465226.35469707
     2219466.297      465096.6182219551.16427176 464889.32591007
 2219412.5208505464725.0721861562219409.52957671 464661.97478801
     2219527.158      464603.248     2219603.319      464463.964
     2219615.551      464303.697     2220075.972      463729.926
2220160.75607034463500.167365323     2220428.357      463278.996

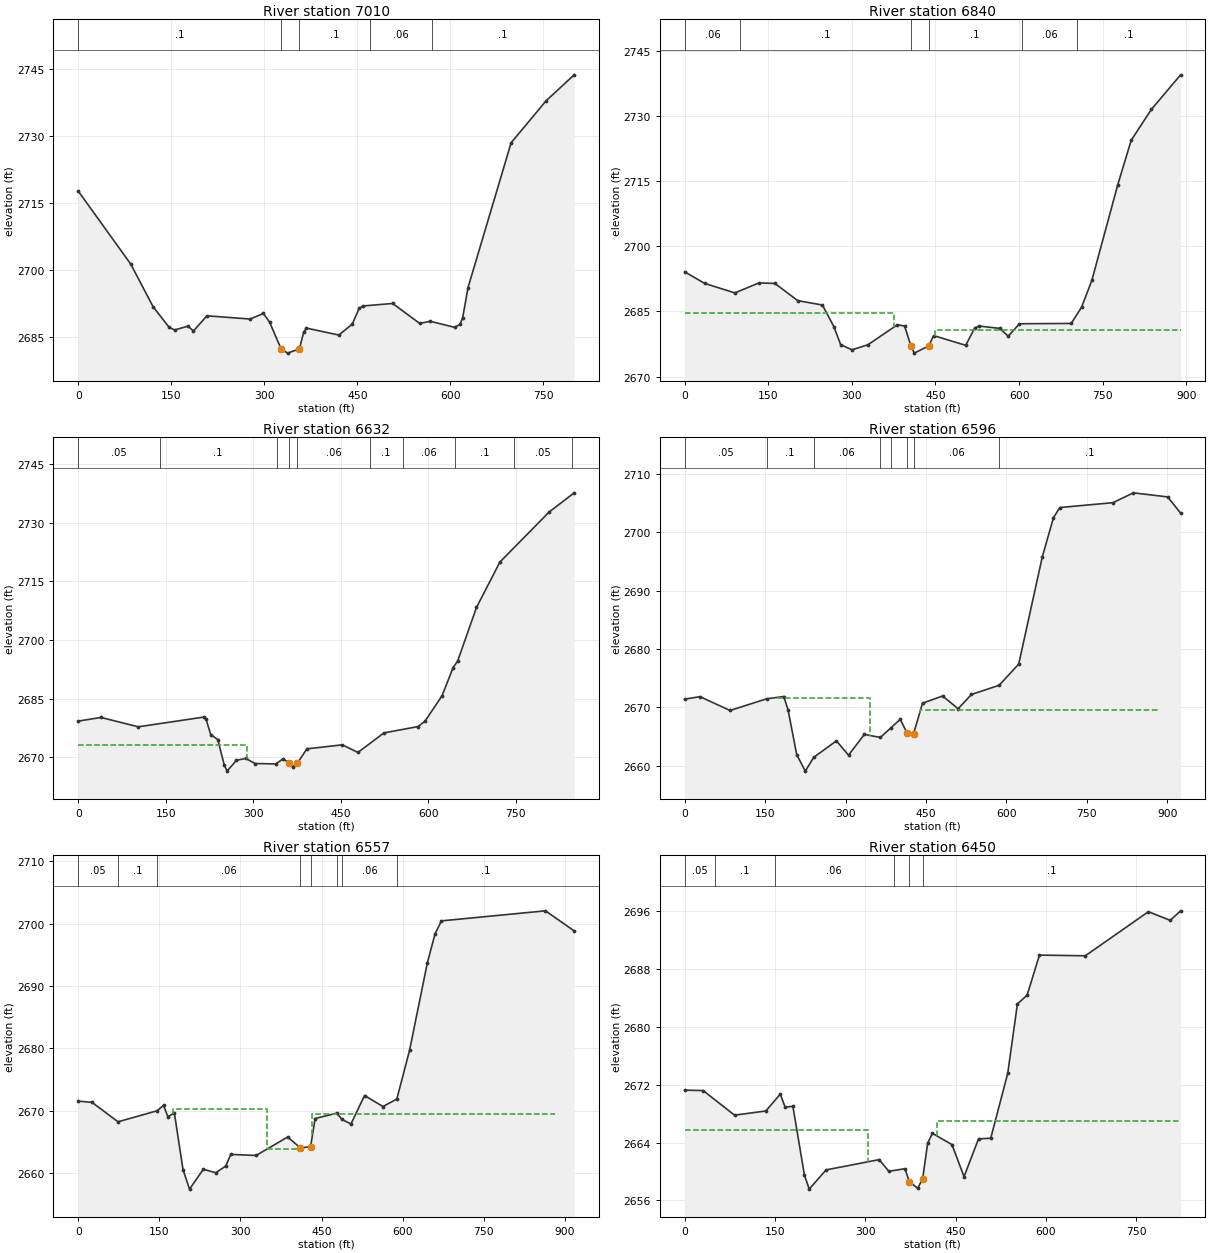
Type RM Length L Ch R = 1 ,7010    ,169.9,169.9,169.9
XS GIS Cut Line= 2
2220059.37693875469252.865964336     2219322.464      468942.641
#Sta/Elev= 30
       0 2717.62    84.7 2701.26   120.7 2691.73   146.7 2687.08   155.4 2686.52
   177.1 2687.37   185.8 2686.28   207.5 2689.69   277.1 2688.96   298.6 2690.22
   308.5 2688.27  327.262682.226   337.7 2681.33   356.5 2682.28   363.7  2686.1
     368 2686.93   420.1 2685.38   441.8 2687.81   452.8 2691.35   459.2 2691.89
   506.9 2692.45   550.3    2688   567.7 2688.45   606.7 2687.11   615.4 2687.75
   619.8 2689.25   628.4    2696   697.9 2728.43   754.3 2737.83   799.5 2743.64
#Mann= 5 ,-1,0
       0      .1       0  327.26    .045       0   356.5      .1       0
     470     .06       0     570      .1       0
Bank Sta=327.26,356.5
XS Rating Curve= 0 ,0
Exp/Cntr=0.3,0.1

Type RM Length L Ch R = 1 ,6840    ,216.4,208.1,192.2
XS GIS Cut Line= 4
2220223.52356781468913.0623285122219849.63032098468981.106839844
2219771.80059879468948.430238923 2219347.8734288468913.967861231
#Sta/Elev= 30
       0 2694.13    35.9 2691.45      90 2689.27   133.5 2691.58     162 2691.44
   202.8 2687.49   247.2 2686.47   267.7 2681.49   279.9 2677.34   300.2 2676.16
   328.7 2677.31   381.6 2681.93   394.6 2681.63  405.682677.124     412 2675.39
437.72862677.052   446.7 2679.43   504.2 2677.19   520.3 2681.17   528.3 2681.63
   565.3 2681.09   580.5 2679.29   600.7 2682.16   693.5 2682.23   712.1 2685.97
   730.6 2692.18   777.1 2714.22   801.1 2724.43   837.3 2731.55   889.8 2739.52
#Mann= 6 ,-1,0
       0     .06       0     100      .1       0  405.68    .045       0
437.7286      .1       0  604.45     .06       0  704.45      .1       0
#XS Ineff= 2 , 0
          375.77 2684.75  449.58         2680.78
Permanent Ineff=
       F       F
Bank Sta=405.68,437.7286
XS Rating Curve= 0 ,0
Exp/Cntr(USF)=0,0
Exp/Cntr=0.3,0.1

Type RM Length L Ch R = 1 ,6632    ,36.4,35.2,34.6
BEGIN DESCRIPTION:
structure xs 4
END DESCRIPTION:
XS GIS Cut Line= 5
2220167.15505026468775.9347797122219815.85797424468765.223757028
2219759.16074066468776.5164386822219636.34123497468836.735675772
2219333.21571598468858.817927389
#Sta/Elev= 30
       0 2679.22      39 2680.16     103 2677.76   215.1 2680.25   219.1 2679.72
   227.1 2675.77   239.1 2674.51   250.2 2668.09   255.1 2666.42   271.1 2669.18
   287.1 2669.67   303.1 2668.37   338.7 2668.26   351.1 2669.56   361.4 2668.53
   367.5 2667.45   375.6 2668.43   391.9 2672.12   452.7 2673.15   479.4  2671.2
     524  2676.2   582.3 2677.82   594.4  2679.2   623.6 2685.72   642.5 2692.88
   650.5 2694.66   682.6  2708.3   722.7 2719.92   806.9  2732.7     850 2737.64
#Mann= 10 ,-1,0
       0     .05       0     140      .1       0     340     .06       0
   361.4    .045       0   375.6     .06       0  499.27      .1       0
  556.06     .06       0  646.06      .1       0  746.06     .05       0
  846.06      .1       0
#XS Ineff= 2 , 0
          288.55 2673.14
Permanent Ineff=
       F       F
Bank Sta=361.4,375.6
XS Rating Curve= 0 ,0
Exp/Cntr(USF)=0,0
Exp/Cntr=0.5,0.3

Type RM Length L Ch R = 1 ,6596    ,40.2,39.7,39
BEGIN DESCRIPTION:
structure xs 3; 12.3 ft between structure and xs
END DESCRIPTION:
XS GIS Cut Line= 6
2220168.61783698468649.697437709 2219920.3983357468633.050426493
2219877.37777047468695.3170340692219823.60206393468725.318217719
2219651.11772431468772.693029822     2219334.873      468600.858
#Sta/Elev= 30
       0  2671.4    28.5 2671.83    84.6 2669.46   152.8 2671.46   184.9 2671.85
   192.9 2669.51   208.9  2661.9   224.9 2659.07   240.6 2661.43     283 2664.26
   305.5  2661.8     335 2665.36   364.9 2664.84   384.9 2666.52     402 2667.95
   414.7  2665.6   426.9  2665.5   443.5 2670.71   480.9 2671.94   509.9 2669.76
   534.8 2672.21   586.5 2673.78   622.9 2677.42     667 2695.83   687.7 2702.49
   699.5 2704.23   798.5 2705.06   836.8 2706.75   900.6 2706.05   924.8 2703.28
#Mann= 8 ,-1,0
       0     .05       0   152.8      .1       0   240.6     .06       0
   364.9      .1       0   384.9     .06       0   414.7    .045       0
   426.9     .06       0   586.5      .1       0
#XS Ineff= 4 ,-1
       0  172.96  2663.9  172.96  346.48 2671.52  346.48     402  2663.9
     438   881.8  2669.5
Permanent Ineff=
       F       F       F       F
Bank Sta=414.7,426.9
XS Rating Curve= 0 ,0
Exp/Cntr=0.5,0.3

Type RM Length L Ch R = 1 ,6557    ,103.3,106.5,111.4
BEGIN DESCRIPTION:
structure xs 2; 10 ft between structure and xs
END DESCRIPTION:
XS GIS Cut Line= 6
2220165.69277923468618.8341250152219898.32199302 468604.74742305
2219874.54747012468645.5037480092219835.73413435468679.806047997
2219653.76844438 468735.064696222219337.52372008468563.229666398
#Sta/Elev= 30
       0 2671.55    25.6 2671.35    73.6 2668.23   145.7    2670   157.7 2670.86
   165.7 2669.06   177.8 2669.62   193.8 2660.53   205.8 2657.43   231.3 2660.62
   254.2 2660.06   272.6 2661.12   282.1    2663   328.8 2662.83   387.2 2665.79
  410.532664.056  429.54 2664.23     438 2668.76   478.1 2669.62   487.5 2668.62
   504.2 2667.88   529.3 2672.45   563.3 2670.68     589 2671.88   612.6 2679.72
   645.2 2693.65   659.7 2698.41   671.5 2700.47   863.7 2702.08   916.8 2698.86
#Mann= 8 ,-1,0
       0     .05       0    73.6      .1       0   145.7     .06       0
  410.53    .045       0  429.54     .06       0   478.1      .1       0
   487.5     .06       0     589      .1       0
#XS Ineff= 4 ,-1
       0  175.21  2663.9  175.21   349.3 2670.26   349.3     407  2663.9
     433   881.5  2669.5
Permanent Ineff=
       F       F       F       F
Bank Sta=410.53,429.54
XS Rating Curve= 0 ,0
Exp/Cntr=0.5,0.3

Type RM Length L Ch R = 1 ,6450    ,187.9,189,188.3
BEGIN DESCRIPTION:
structure xs 1
END DESCRIPTION:
XS GIS Cut Line= 3
 2220170.8858025468608.1137370852219854.16930765468597.388642155
2219351.10278203468537.968680137
#Sta/Elev= 30
       0 2671.25    30.7 2671.19    82.8 2667.79   134.8 2668.37   158.8 2670.71
   166.8 2668.89   179.7 2669.01   198.8 2659.52   206.8 2657.56   234.8 2660.22
   322.9 2661.64     339 2660.03   365.7 2660.38373.05422658.594   386.9 2657.68
395.15422658.977   403.5 2663.95   411.5 2665.27   443.8 2663.72   463.9 2659.28
   487.9 2664.51   508.2  2664.6   536.4 2673.56   552.5 2683.18   568.6 2684.38
   589.1 2689.93   665.3 2689.83     770 2695.93   806.3 2694.73   823.5 2696.05
#Mann= 6 ,-1,0
       0     .05       0      50      .1       0     150     .06       0
   346.9      .1       0373.0542    .045       0395.1542      .1       0
#XS Ineff= 2 , 0
          304.79 2665.67  418.59         2666.92
Permanent Ineff=
       F       F
Bank Sta=373.0542,395.1542
XS Rating Curve= 0 ,0
Exp/Cntr(USF)=0,0
Exp/Cntr=0.3,0.1

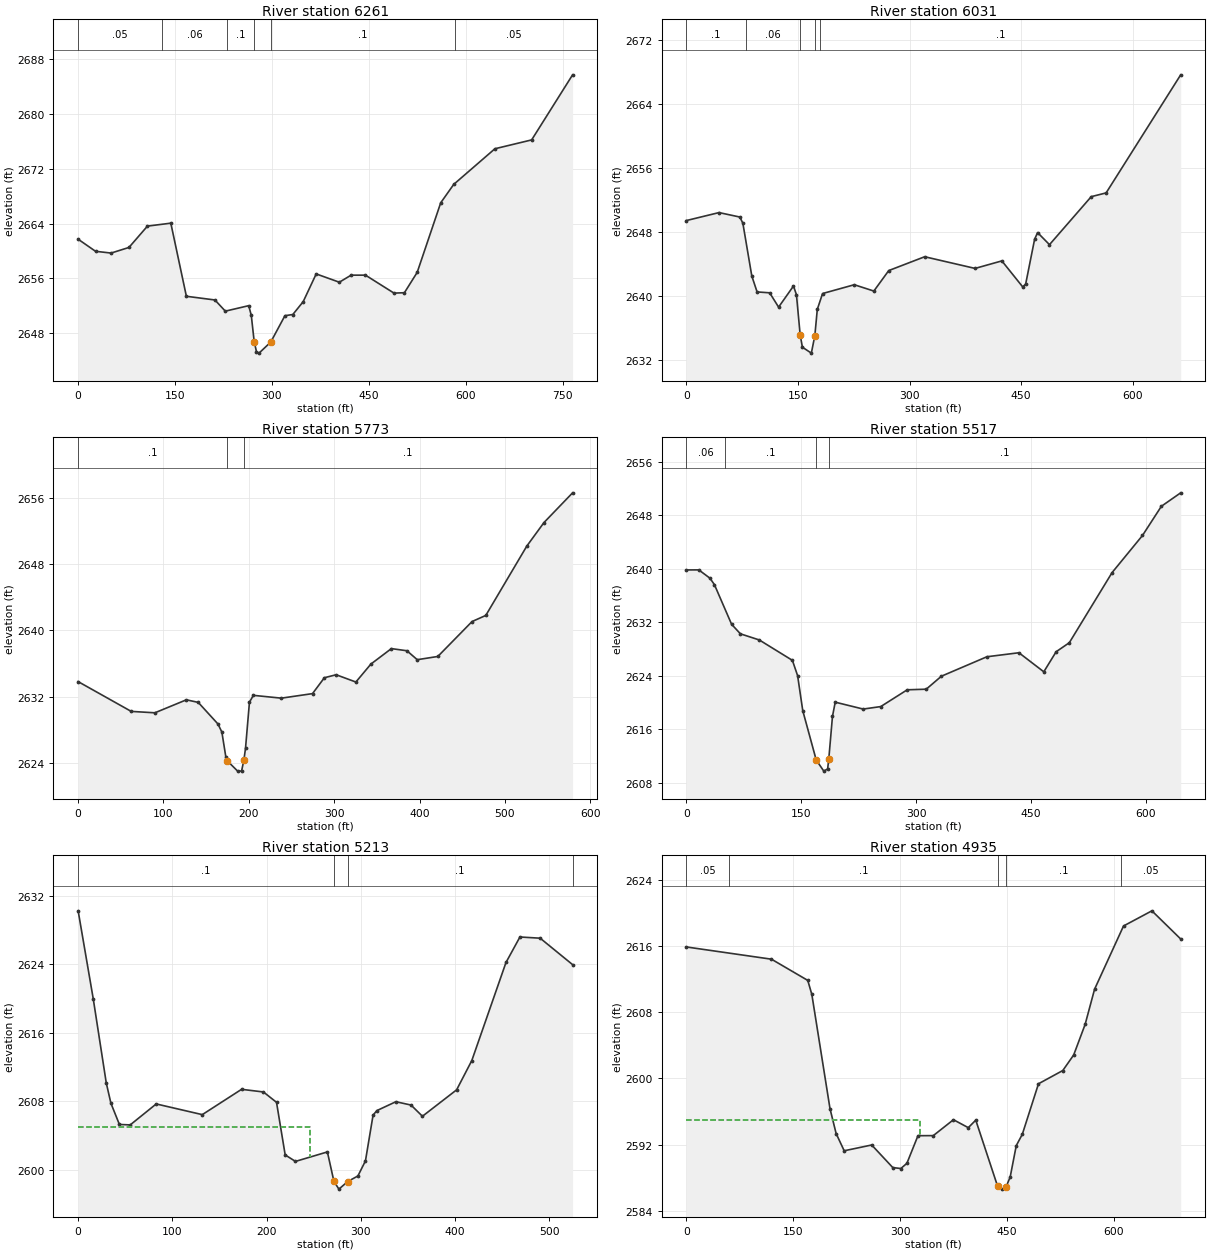
Type RM Length L Ch R = 1 ,6261    ,229.9,230.7,228
XS GIS Cut Line= 3
 2220150.9655677468464.3529931192219630.63964945468413.286523689
 2219389.1090508468438.129670979
#Sta/Elev= 30
       0 2661.72    26.9 2659.96      51  2659.7    78.7 2660.52   107.3 2663.63
   143.5 2664.06   167.6  2653.4   211.8 2652.86   227.9 2651.23   264.1 2652.03
   268.1 2650.62   272.6 2646.78   276.1 2645.34   280.1 2645.11   298.3 2646.73
   320.2 2650.57   332.4 2650.74   348.5 2652.62   368.6 2656.66   404.4 2655.45
   422.7 2656.48   444.9 2656.48   489.1 2653.86   505.2 2653.92     525 2656.89
   561.4 2667.03   581.6 2669.72   645.3 2674.91   702.2  2676.2   765.6 2685.69
#Mann= 6 ,-1,0
       0     .05       0     130     .06       0     230      .1       0
   272.6    .045       0   298.3      .1       0  582.83     .05       0
Bank Sta=272.6,298.3
XS Rating Curve= 0 ,0
Exp/Cntr(USF)=0,0
Exp/Cntr=0.3,0.1

Type RM Length L Ch R = 1 ,6031    ,264.1,257.6,250
XS GIS Cut Line= 2
2220104.22296353468218.358629458     2219439.996      468231.804
#Sta/Elev= 30
       0 2649.46    44.1 2650.46    72.1  2649.9    76.1 2649.12    88.1 2642.53
    95.2 2640.54   112.1 2640.43   124.1 2638.64   144.1 2641.28   148.1 2640.19
153.07582635.174   156.1 2633.63   168.1 2632.89   172.8 2635.07   176.1 2638.36
   183.2 2640.34   225.8 2641.44   252.1 2640.65   272.1 2643.21   320.4 2644.94
   388.1 2643.48   424.1 2644.42   452.1 2641.17   456.1 2641.53   468.1 2647.12
   472.1 2647.96   488.1 2646.45   544.2 2652.45   564.2 2652.92   664.4 2667.68
#Mann= 5 ,-1,0
       0      .1       0      80     .06       0153.0758    .045       0
   172.8     .06       0     180      .1       0
Bank Sta=153.0758,172.8
XS Rating Curve= 0 ,0
Exp/Cntr=0.3,0.1

Type RM Length L Ch R = 1 ,5773    ,254.7,256,253.5
XS GIS Cut Line= 3
 2220006.0472085467917.8037527352219673.42506978468109.648056809
2219478.82041601468126.210155002
#Sta/Elev= 30
       0 2633.82    62.2 2630.22    89.9 2630.05   126.8 2631.62   140.7 2631.31
   163.8  2628.7   168.4 2627.72     173 2624.74   174.9 2624.23   186.9    2623
   191.5 2623.01   194.2 2624.35   196.1 2625.76   200.7 2631.33   205.3 2632.16
   238.1 2631.82   274.6 2632.37   288.5 2634.29   302.3 2634.65   325.4 2633.77
     343 2635.94     367 2637.81   385.2 2637.55   397.3 2636.47   421.4 2636.86
   461.5 2641.08   477.6 2641.82   525.7 2650.21   545.8 2653.05   579.3 2656.64
#Mann= 3 ,-1,0
       0      .1       0   174.9    .045       0   194.2      .1       0
Bank Sta=174.9,194.2
XS Rating Curve= 0 ,0
Exp/Cntr(USF)=0,0
Exp/Cntr=0.3,0.1

Type RM Length L Ch R = 1 ,5517    ,298.7,304.3,310.6
XS GIS Cut Line= 2
2219965.25092323467655.4882899472219443.86618295468035.983741084
#Sta/Elev= 30
       0 2639.83    16.4 2639.84      31 2638.59    36.8 2637.63    59.2 2631.71
    70.7 2630.28    95.4 2629.36   138.6 2626.31   145.4 2624.02   152.1  2618.8
   169.7 2611.41   179.6 2609.75   184.6 2610.08   186.1 2611.57   190.9 2617.93
   194.5 2620.06     231 2619.03   253.9  2619.4   288.5 2621.91   313.3    2622
   333.1 2623.94   392.5 2626.85   434.3 2627.45   466.8  2624.6   482.9  2627.6
   500.1 2628.95   555.9 2639.43   595.6 2644.98   620.3 2649.35   645.5 2651.36
#Mann= 4 ,-1,0
       0     .06       0      50      .1       0   169.7    .045       0
   186.1      .1       0
Bank Sta=169.7,186.1
XS Rating Curve= 0 ,0
Exp/Cntr=0.3,0.1

Type RM Length L Ch R = 1 ,5213    ,283.8,277.6,270.5
XS GIS Cut Line= 3
 2219825.9592338467471.3599743562219605.61293891467600.146849909
2219337.97771315467633.349716262
#Sta/Elev= 30
       0 2630.26      16    2620    29.9 2610.11    34.8 2607.76    43.8 2605.28
    55.3 2605.23    82.9 2607.68   131.8 2606.43   173.5 2609.39   196.7 2609.08
   210.6 2607.87   219.8 2601.72   230.7 2600.96   264.6 2602.07   271.52598.648
   276.8 2597.72   286.22598.606     297 2599.26     305 2601.02   313.1 2606.37
   317.1  2606.9   337.3 2607.94   353.4 2607.55   365.5 2606.24   401.8 2609.33
   417.9 2612.75   454.2 2624.22     469  2627.2   490.5 2627.06   524.9 2623.97
#Mann= 4 ,-1,0
       0      .1       0   271.5    .045       0   286.2      .1       0
  524.91     .05       0
#XS Ineff= 2 , 0
          246.18 2604.95
Permanent Ineff=
       F       F
Bank Sta=271.5,286.2
XS Rating Curve= 0 ,0
Exp/Cntr(USF)=0,0
Exp/Cntr=0.3,0.1

Type RM Length L Ch R = 1 ,4935    ,188.6,193.4,198.1
XS GIS Cut Line= 2
2219803.96598618 467100.830705072219271.44164667467545.334349236
#Sta/Elev= 30
       0 2615.88   119.6  2614.4   170.5 2611.84   176.2 2610.15   201.7 2596.35
   210.3 2593.35   221.6 2591.27   260.2 2591.97   289.8 2589.24   301.1 2589.13
   309.6 2589.76   325.1 2593.09   346.6  2593.1   374.9 2595.02   395.7 2594.06
   406.2 2594.97   436.9 2586.97   443.7 2586.64   448.8 2586.93   454.5 2588.11
     463 2591.89   471.5 2593.26   494.2 2599.36   528.3 2600.96   543.6 2602.84
   559.6 2606.52   572.9 2610.78   613.5 2618.41   653.3 2620.24   693.7 2616.84
#Mann= 5 ,-1,0
       0     .05       0      60      .1       0   436.9    .045       0
   448.8      .1       0     610     .05       0
#XS Ineff= 2 , 0
          327.72    2595
Permanent Ineff=
       F       F
Bank Sta=436.9,448.8
XS Rating Curve= 0 ,0
Exp/Cntr=0.3,0.1

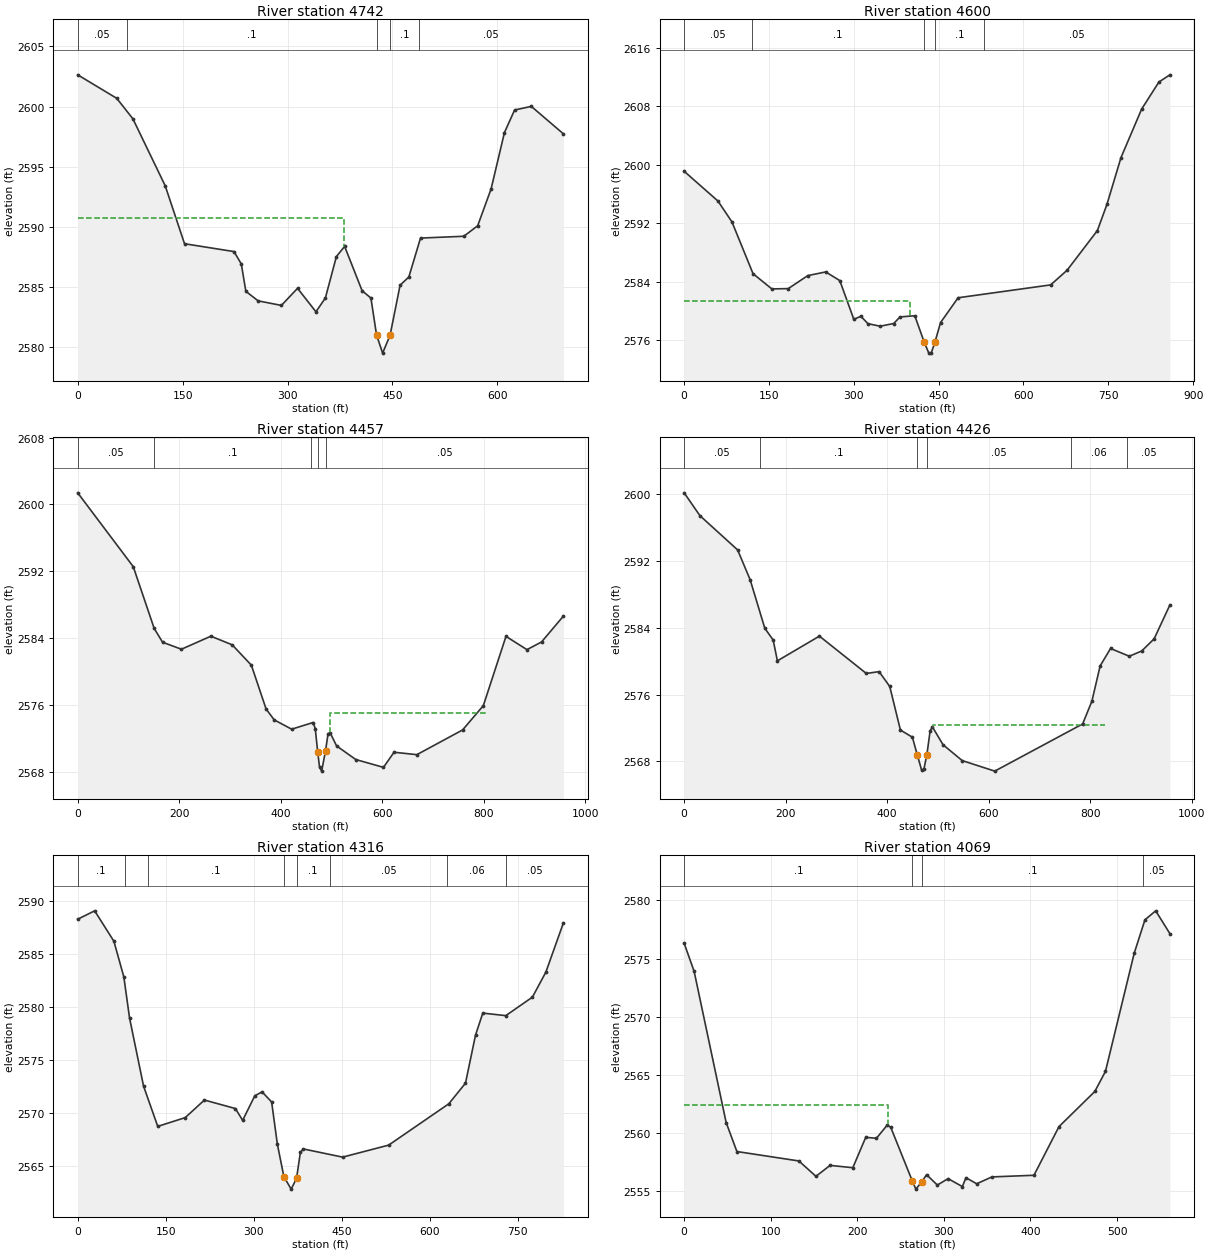
Type RM Length L Ch R = 1 ,4742    ,141,141.5,141.8
XS GIS Cut Line= 4
2219760.55964855 467008.532140342219407.40188825467211.773928321
  2219298.737962467243.9706472092219153.85272701467339.554656408
#Sta/Elev= 30
       0 2602.63    55.8 2600.68    78.9 2598.98   125.1 2593.42   152.7 2588.61
   223.4 2587.96   233.9 2586.93   240.4 2584.66   257.9 2583.87   291.2 2583.49
   314.3 2584.91   340.6 2582.96   354.1 2584.11   369.8 2587.54   381.6 2588.39
   406.6 2584.71   419.2  2584.1   427.22581.049   435.9 2579.53   446.6 2581.02
   460.9 2585.17   473.4 2585.85   490.1 2589.08     552 2589.23   571.8  2590.1
     591 2593.16   610.1 2597.84   624.6 2599.71   648.5 2600.01   694.4 2597.73
#Mann= 5 ,-1,0
       0     .05       0      70      .1       0   427.2    .045       0
   446.6      .1       0  487.46     .05       0
#XS Ineff= 2 , 0
          380.56 2590.72
Permanent Ineff=
       F       F
Bank Sta=427.2,446.6
XS Rating Curve= 0 ,0
Exp/Cntr(USF)=0,0
Exp/Cntr=0.3,0.1

Type RM Length L Ch R = 1 ,4600    ,135.4,142.8,150.3
BEGIN DESCRIPTION:
structure xs 4
END DESCRIPTION:
XS GIS Cut Line= 2
2219749.78795782 466974.638500682218920.72244645 467199.00938543
#Sta/Elev= 30
       0 2599.12    59.7 2595.06    84.5  2592.2   121.8 2585.12     155 2583.04
     184 2583.08   218.6 2584.86   250.3 2585.36   275.2 2584.18     300 2578.88
   312.5  2579.3   324.9 2578.29   346.6 2577.94   370.5 2578.31   381.7 2579.21
   407.8 2579.37   424.1 2575.84   432.6 2574.26   437.1 2574.32   443.7 2575.84
   453.4 2578.44   484.4 2581.83   648.1 2583.59   677.1 2585.59   730.7 2591.02
   747.6  2594.6   772.4 2600.99   808.9 2607.62   839.5 2611.33   858.9 2612.31
#Mann= 5 ,-1,0
       0     .05       0     120      .1       0   424.1    .045       0
   443.7      .1       0     530     .05       0
#XS Ineff= 2 , 0
          398.87 2581.41
Permanent Ineff=
       F       F
Bank Sta=424.1,443.7
XS Rating Curve= 0 ,0
Exp/Cntr(USF)=0,0
Exp/Cntr=0.5,0.3

Type RM Length L Ch R = 1 ,4457    ,31.8,31.6,31.6
BEGIN DESCRIPTION:
structure xs 3; 7.2 ft between structure and xs
END DESCRIPTION:
XS GIS Cut Line= 4
     2219778.309      466960.7482219536.48469519467021.927431547
2219190.36996714466911.251210369     2218854.106      466984.898
#Sta/Elev= 30
       0 2601.38   109.5 2592.54   150.7 2585.15   167.2  2583.5   204.4 2582.66
   262.4 2584.22   304.4 2583.19   342.2 2580.75   371.2 2575.51   387.1 2574.21
   421.6 2573.09   463.9 2573.89   468.1 2573.16     473  2570.3   476.5 2568.57
   480.7 2568.07   488.3  2570.5   493.3 2572.54   497.5 2572.65   510.1 2571.09
   547.9 2569.46   602.5 2568.52   623.3 2570.33   668.3 2570.04   758.4    2573
   799.3 2575.91   843.9  2584.2   885.3 2582.61     914 2583.53   957.1 2586.63
#Mann= 5 ,-1,0
       0     .05       0     150      .1       0  459.44     .05       0
     473    .045       0   488.3     .05       0
#XS Ineff= 4 ,-1
       0     466  2570.3   495.5  497.46  2568.3  497.46  804.51    2575
  804.51   957.1  2568.3
Permanent Ineff=
       F       F       F       F
Bank Sta=473,488.3
XS Rating Curve= 0 ,0
Exp/Cntr=0.5,0.3

Type RM Length L Ch R = 1 ,4426    ,118.3,109.5,102.2
BEGIN DESCRIPTION:
structure xs 2; 11.9 ft between structure and xs
END DESCRIPTION:
XS GIS Cut Line= 4
 2219778.2399003466927.5451336472219536.41559548466988.724565194
2219190.30086744466878.048344016 2218854.0369003466951.695133647
#Sta/Elev= 30
       0 2600.14      31 2597.41   105.3 2593.31     130 2589.74   158.9 2583.93
   175.4 2582.52   183.7 2580.03   266.5 2582.99   358.9 2578.52   384.1 2578.74
   405.1 2576.96   426.1 2571.75   449.7 2570.89   459.3 2568.78   468.1 2566.91
   472.3 2567.05   478.32568.807   484.7 2571.67   489.1 2572.13   510.1 2569.99
   547.9 2568.09     612 2566.83   785.2 2572.48   803.4  2575.2   819.7 2579.43
   840.2 2581.51   877.1 2580.58   901.6 2581.21   926.1 2582.67   957.1 2586.72
#Mann= 6 ,-1,0
       0     .05       0     150      .1       0   459.3    .045       0
   478.3     .05       0  762.82     .06       0  872.82     .05       0
#XS Ineff= 4 ,-1
       0   455.3  2569.6   482.3  490.14  2568.3  490.14   829.3 2572.38
   829.3   957.1  2568.3
Permanent Ineff=
       F       F       F       F
Bank Sta=459.3,478.3
XS Rating Curve= 0 ,0
Exp/Cntr=0.5,0.3

Type RM Length L Ch R = 1 ,4316    ,246.5,247,247
BEGIN DESCRIPTION:
structure xs 1
END DESCRIPTION:
XS GIS Cut Line= 2
2219648.16706383466725.1139292982218847.27368149466936.404897001
#Sta/Elev= 30
       0 2588.25    28.9 2589.04    61.7 2586.18    78.7 2582.82    88.4 2578.96
   112.3 2572.55   136.5 2568.76   183.4 2569.59   216.1 2571.24   268.9 2570.44
   281.3 2569.33     302 2571.64   314.4 2572.01   330.7 2571.06   340.5 2567.08
   351.6 2564.03     364 2562.86   373.2 2563.87   379.7 2566.31   384.7 2566.64
   451.8 2565.87   530.3    2567   632.9 2570.89   661.3 2572.83   678.4 2577.35
   690.8 2579.42     730 2579.18   775.4 2580.92   798.4 2583.28   828.3 2587.91
#Mann= 8 ,-1,0
       0      .1       0      80     .06       0     120      .1       0
   351.6    .045       0   373.2      .1       0     430     .05       0
     630     .06       0     730     .05       0
Bank Sta=351.6,373.2
XS Rating Curve= 0 ,0
Exp/Cntr(USF)=0,0
Exp/Cntr=0.3,0.1

Type RM Length L Ch R = 1 ,4069    ,160.9,164.3,166.6
XS GIS Cut Line= 2
2219495.09525687466514.4668263472218952.27248858  466656.0727659
#Sta/Elev= 30
       0 2576.32    11.5 2573.91    48.5 2560.92    60.9 2558.43   132.5 2557.62
   152.2  2556.3   168.5 2557.24   194.8 2557.04   209.7 2559.65   222.1 2559.57
   234.5  2560.7   238.6 2560.51   263.6 2555.88   267.6  2555.2   274.3 2555.82
     280 2556.44   292.4 2555.55   304.8  2556.1   321.3 2555.42   325.5 2556.18
   337.9 2555.66   355.4 2556.25     404 2556.39   432.9 2560.57   474.3 2563.59
   486.6 2565.32   519.8 2575.47   532.2 2578.34   544.6 2579.11     561 2577.15
#Mann= 4 ,-1,0
       0      .1       0   263.6    .045       0   274.3      .1       0
     530     .05       0
#XS Ineff= 2 , 0
          235.27 2562.45
Permanent Ineff=
       F       F
Bank Sta=263.6,274.3
XS Rating Curve= 0 ,0
Exp/Cntr(USF)=0,0
Exp/Cntr=0.3,0.1

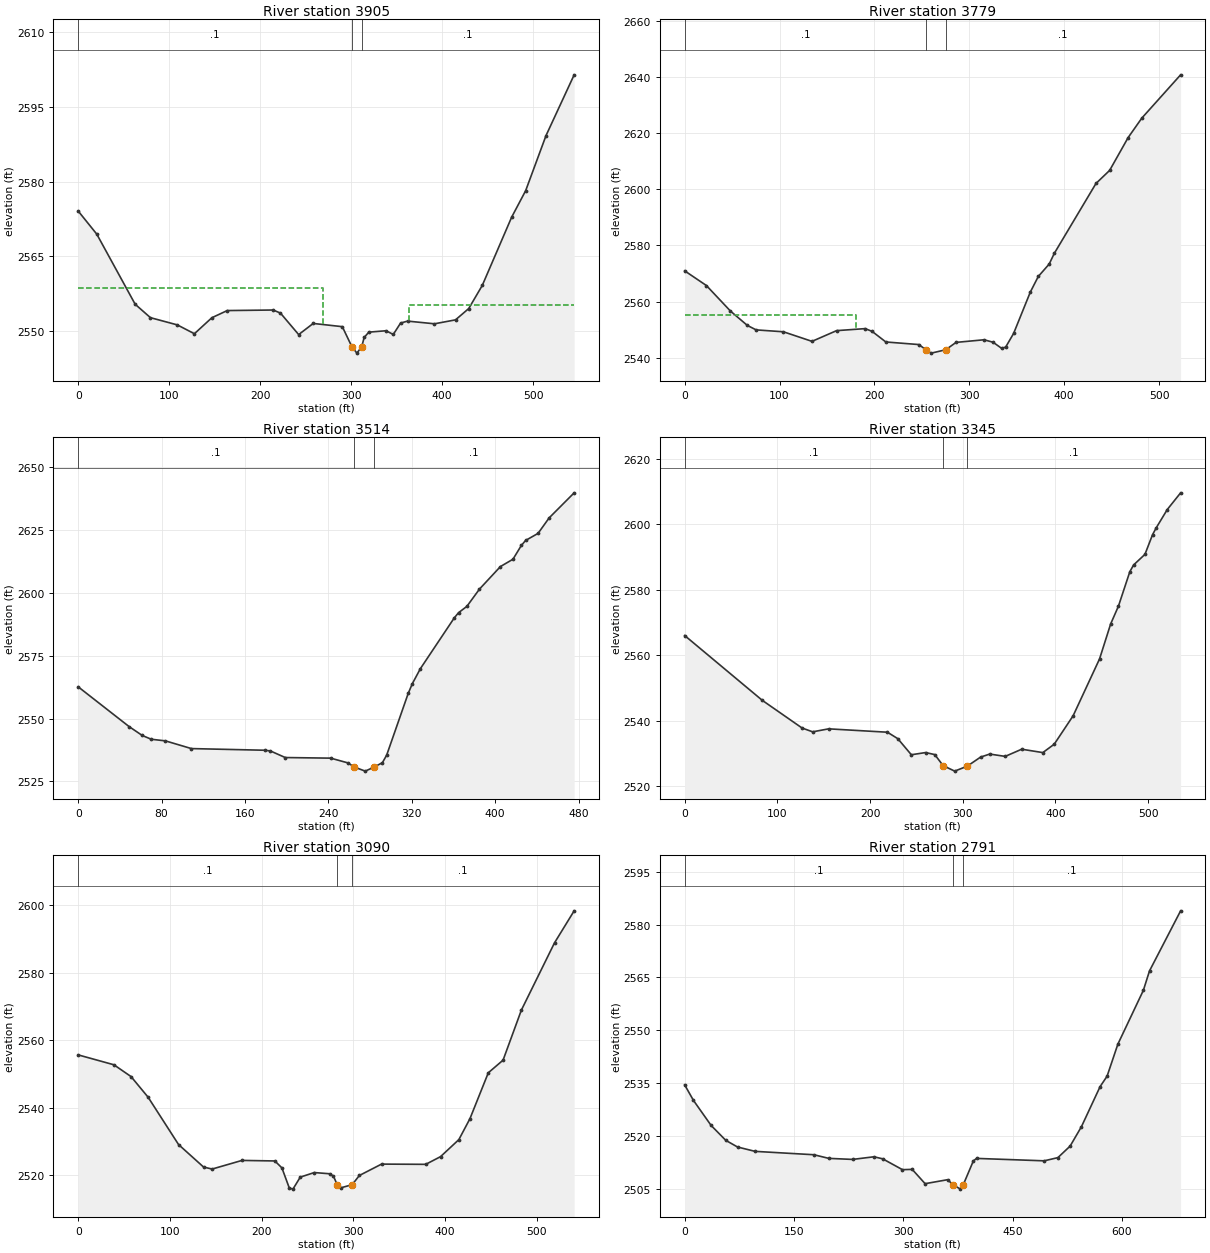
Type RM Length L Ch R = 1 ,3905    ,121.8,126.2,130.2
XS GIS Cut Line= 4
2219427.52483756466396.7944814672219225.28919704466464.206361638
2219057.26257034466461.1879192432218913.38348281466382.708416953
#Sta/Elev= 30
       0 2574.08    20.4 2569.44    62.6 2555.34    79.4 2552.64   108.9 2551.19
   127.7 2549.41   146.9 2552.63   163.8 2554.07   214.3 2554.18   222.3 2553.56
   242.3 2549.24   258.3 2551.48   290.3 2550.83   300.72546.834   306.3 2545.51
   311.6  2546.8   314.3 2548.66   319.4 2549.73   338.3 2550.01   346.3 2549.27
   354.3 2551.55     362 2551.95   391.6 2551.41   414.7  2552.2   429.2 2554.47
   444.1 2559.12   476.4 2572.85   491.8 2578.18   514.2 2589.27   545.1 2601.48
#Mann= 3 ,-1,0
       0      .1       0   300.7    .045       0   311.6      .1       0
#XS Ineff= 2 , 0
           269.1 2558.61  363.04         2555.13
Permanent Ineff=
       F       F
Bank Sta=300.7,311.6
XS Rating Curve= 0 ,0
Exp/Cntr(USF)=0,0
Exp/Cntr=0.3,0.1

Type RM Length L Ch R = 1 ,3779    ,265.4,264.5,259.9
XS GIS Cut Line= 4
2219413.00210962466308.3116631032219240.45299715466376.587358886
2219078.97253976466307.0265464742218925.23955144466258.170915783
#Sta/Elev= 30
       0 2570.95    22.9 2565.72    48.2 2556.65      66 2551.54    75.3 2549.94
   104.1 2549.26   134.2 2545.86   160.1 2549.67   190.2 2550.39   197.5 2549.42
     212 2545.64   246.8 2544.72   254.8 2542.74   259.9 2541.67   275.1 2542.86
     286 2545.49   315.5 2546.42     325 2545.55     334 2543.39   338.3 2543.81
   346.7 2548.69   364.3  2563.4   372.7 2568.95   384.2 2573.37   389.5 2577.13
   433.5 2602.04   447.9 2606.69   467.4 2618.37   481.8 2625.29   522.7 2640.69
#Mann= 3 ,-1,0
       0      .1       0   254.8    .045       0   275.1      .1       0
#XS Ineff= 2 , 0
          180.51 2555.07
Permanent Ineff=
       F       F
Bank Sta=254.8,275.1
XS Rating Curve= 0 ,0
Exp/Cntr=0.3,0.1

Type RM Length L Ch R = 1 ,3514    ,158.6,169.3,178.2
XS GIS Cut Line= 4
2219403.37729839466243.8600667482219212.20927999466101.993274148
2219137.75436756466082.8764723082218977.77692059466066.778112864
#Sta/Elev= 30
       0 2562.61    48.8 2546.82    61.4 2543.29      70 2541.79    83.7 2541.13
   108.6 2538.07     179 2537.41   184.3 2537.14   198.6 2534.51   242.2 2534.27
   258.7 2532.38   264.8 2530.74   275.3 2529.11   283.5 2530.65   291.8 2532.48
   295.9  2535.5   316.5 2559.97   320.5 2563.88   328.2 2569.84   360.7 2590.01
   364.8 2592.08   372.8  2594.6   384.9 2601.47     405 2610.43     417 2613.33
   425.1 2618.84   429.1 2620.79   441.1 2623.62   451.7 2629.76   475.7 2639.73
#Mann= 3 ,-1,0
       0      .1       0   264.8    .045       0   283.5      .1       0
Bank Sta=264.8,283.5
XS Rating Curve= 0 ,0
Exp/Cntr(USF)=0,0
Exp/Cntr=0.3,0.1

Type RM Length L Ch R = 1 ,3345    ,270.9,255.1,236.9
XS GIS Cut Line= 4
2219518.49621781466181.8522534752219360.94226151466079.711748769
2219256.60104289465935.6214944862219090.41150857 465901.99529458
#Sta/Elev= 30
       0 2566.02    83.8 2546.22   126.7 2537.78   138.1 2536.62   155.4 2537.53
   218.8  2536.5     230 2534.53   244.6 2529.62     260 2530.29   269.9 2529.67
   278.9  2526.3   291.4 2524.62     305 2526.14   319.3  2528.9   329.2 2529.83
   345.9 2529.12   363.7 2531.31   386.5 2530.28   398.8 2532.84   419.2 2541.52
   447.7 2558.87   459.7 2569.55   468.1 2574.99   480.4 2585.51   484.5 2587.58
   496.7  2590.8   504.9  2596.8   508.9 2598.92   520.8 2604.49   535.2 2609.59
#Mann= 3 ,-1,0
       0      .1       0   278.9    .045       0     305      .1       0
Bank Sta=278.9,305
XS Rating Curve= 0 ,0
Exp/Cntr=0.3,0.1

Type RM Length L Ch R = 1 ,3090    ,291.8,299.4,305.4
XS GIS Cut Line= 5
2219641.63301816465873.1953405492219466.86520345465769.059077896
2219415.24983848465768.1535451772219326.50763204465779.019937802
 2219130.9125648465763.625881583
#Sta/Elev= 30
       0 2555.64    38.9 2552.72    57.6 2549.23    76.2 2543.13   109.4 2529.13
   136.7 2522.47     146 2521.89   178.6 2524.44   214.4 2524.28   222.1 2522.22
   230.1  2516.3   234.1 2515.95   242.1  2519.5   257.4 2520.85   274.3 2520.49
   278.3 2519.78   282.3 2517.29   286.4 2516.34   298.7 2517.27   306.5 2519.98
   330.7 2523.35   378.9 2523.28     395 2525.55     415 2530.59   427.1 2536.79
   447.1 2550.35   463.2 2554.09   483.2 2568.91   519.3 2588.78   540.7 2598.24
#Mann= 3 ,-1,0
       0      .1       0   282.3    .045       0   298.7      .1       0
Bank Sta=282.3,298.7
XS Rating Curve= 0 ,0
Exp/Cntr(USF)=0,0
Exp/Cntr=0.3,0.1

Type RM Length L Ch R = 1 ,2791    ,176.9,178.4,179
XS GIS Cut Line= 5
2219760.24193181465575.3554350452219601.83756568465558.693810856
2219508.56769565465539.677623763 2219327.4611519465455.463080921
2219111.39268936465522.789295875
#Sta/Elev= 30
       0 2534.49    12.1 2530.06    36.3 2522.96    56.4 2518.73    72.5 2516.84
    96.6  2515.6   177.3 2514.64   197.7 2513.61   230.4 2513.31   259.7 2514.06
   271.7 2513.48   298.8  2510.4   312.2 2510.48   329.9 2506.42   360.8 2507.55
   368.1 2506.15   378.4 2504.87   382.1 2506.03   396.1 2512.88   400.5  2513.6
   493.3 2512.91   512.1 2513.82   528.9  2517.1   544.4 2522.61     570 2533.99
   579.6 2536.96   594.4 2546.06   629.4 2561.36   637.8 2566.87   680.5 2583.94
#Mann= 3 ,-1,0
       0      .1       0   368.1    .045       0   382.1      .1       0
Bank Sta=368.1,382.1
XS Rating Curve= 0 ,0
Exp/Cntr=0.3,0.1