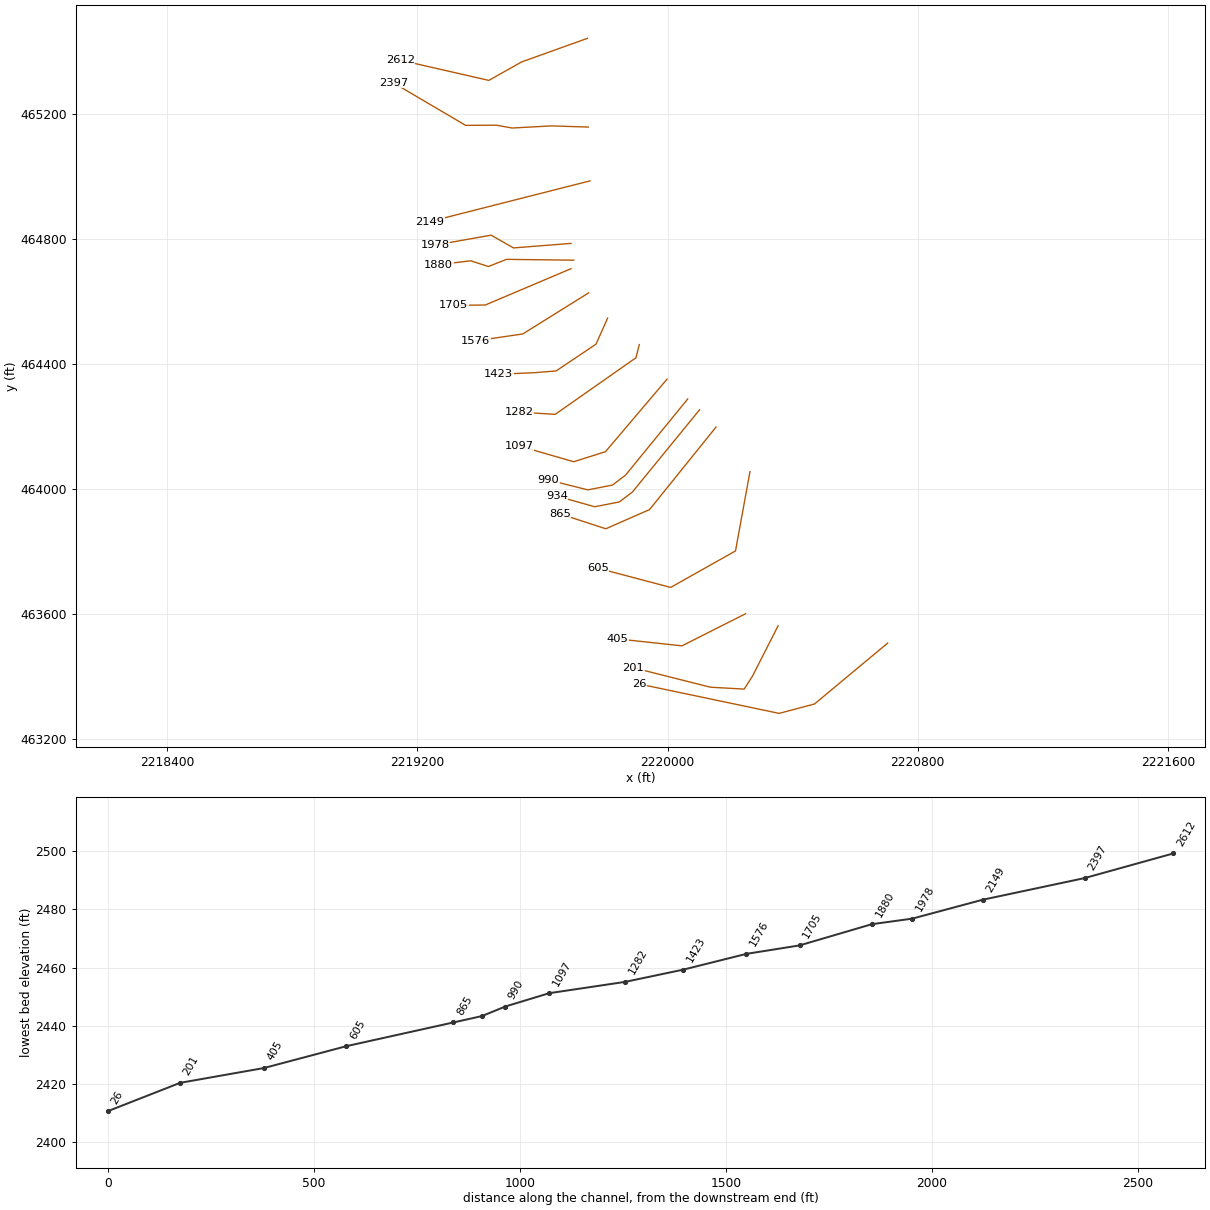
HEC-RAS study STONYCKT1.prj: STONYCKT1

--- STONYCKT1.g01 (geometry) --- (continued)

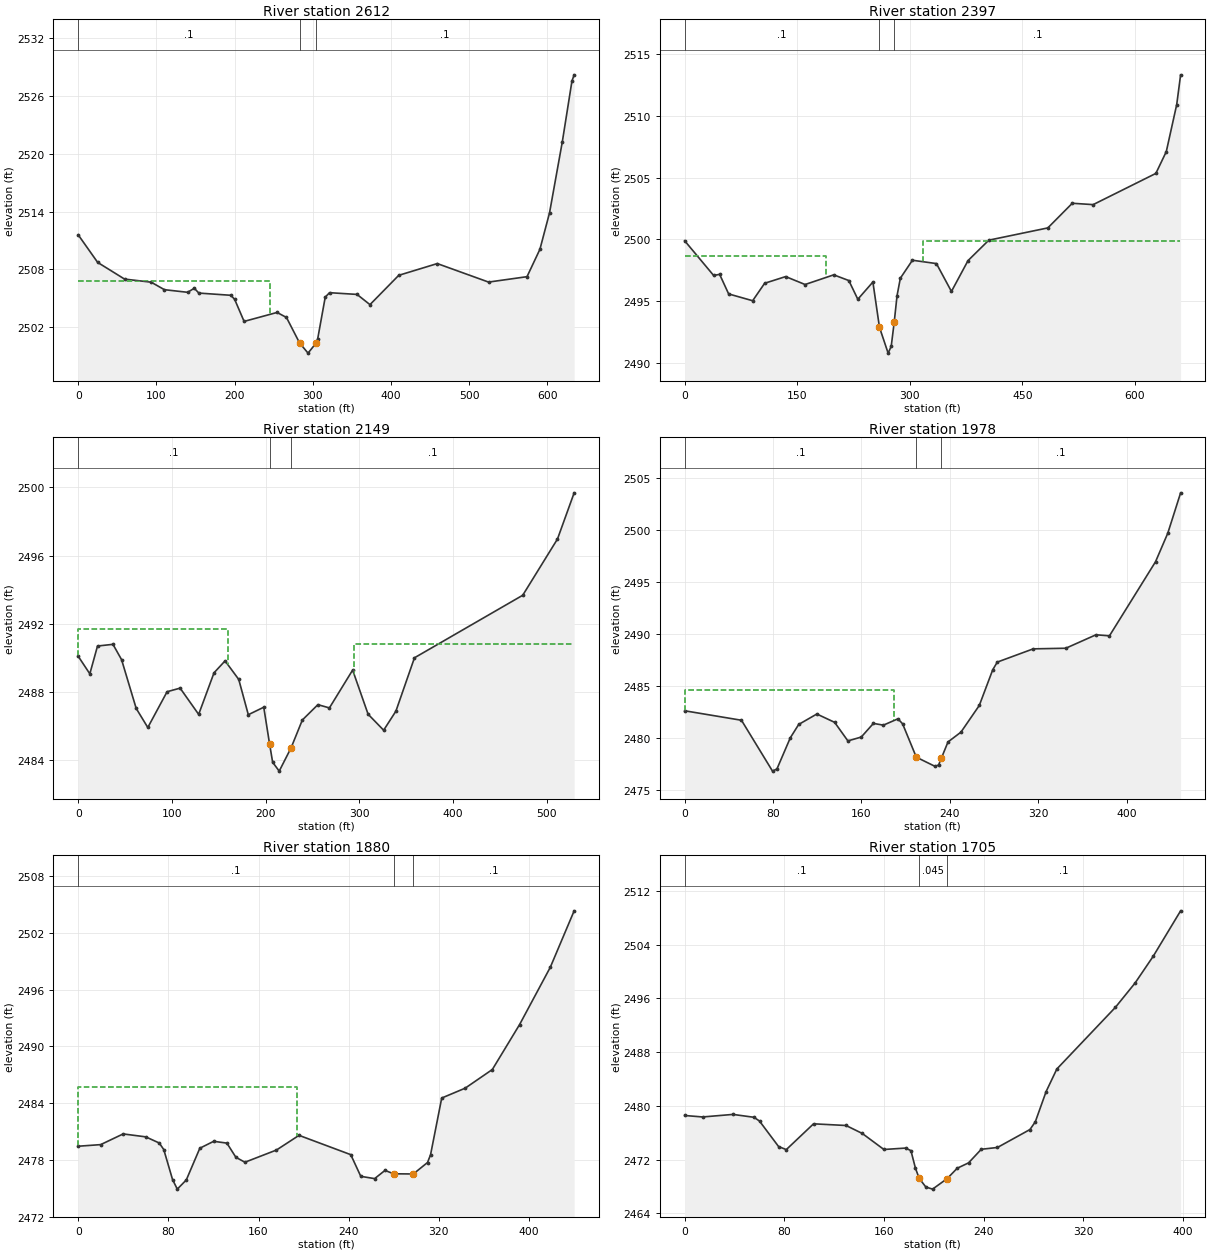
Type RM Length L Ch R = 1 ,2612    ,222.7,215.5,200.7
XS GIS Cut Line= 4
2219743.95821538465441.2562337162219533.76664114465365.872881515
2219428.62920411465306.783119162 2219145.4010883465371.530214374
#Sta/Elev= 30
       0 2511.59    24.9 2508.73    59.3    2507    93.3 2506.68   110.3  2505.9
     140 2505.63   148.5 2506.05   154.3 2505.55   195.2 2505.32   200.1  2504.9
   212.2 2502.61   254.4 2503.54   266.4 2503.02283.22782500.367     294 2499.32
304.49072500.385   306.4 2500.83     316 2505.13   321.5 2505.59   356.7 2505.41
   373.2 2504.35     410 2507.39   459.3 2508.61   524.9 2506.69   574.1 2507.25
   590.6 2510.09   602.9 2513.87   619.3 2521.26   631.6 2527.55   634.4 2528.19
#Mann= 3 ,-1,0
       0      .1       0283.2278    .045       0304.4907      .1       0
#XS Ineff= 2 , 0
           244.9 2506.81
Permanent Ineff=
       F       F
Bank Sta=283.2278,304.4907
XS Rating Curve= 0 ,0
Exp/Cntr(USF)=0,0
Exp/Cntr=0.3,0.1

Type RM Length L Ch R = 1 ,2397    ,240.3,247.6,253
XS GIS Cut Line= 6
2219746.72280067465157.5428164612219629.58052856465161.305681463
 2219503.3491332465154.512960637  2219452.403727465163.569921738
2219354.62713346465162.9760127732219123.73914008465298.869525327
#Sta/Elev= 30
       0 2499.89    38.6 2497.09    46.6 2497.18    58.6  2495.6    90.6 2495.05
   106.6 2496.46   134.6    2497   160.5 2496.36   198.7 2497.14   218.8 2496.68
   230.8 2495.17   250.9 2496.56259.64232492.909   271.2 2490.82   275.3 2491.36
279.28152493.302   283.1 2495.46   287.5 2496.87   303.6 2498.32   335.6 2498.05
   355.6  2495.8   377.7 2498.29   405.4 2499.94   484.1 2500.93   516.7 2502.92
   544.5 2502.81   628.1 2505.33     642 2507.09   655.9 2510.89   661.1 2513.29
#Mann= 3 ,-1,0
       0      .1       0259.6423    .045       0279.2815      .1       0
#XS Ineff= 2 ,-1
       0  188.51 2498.65  318.25     660 2499.85
Permanent Ineff=
       F       F
Bank Sta=259.6423,279.2815
XS Rating Curve= 0 ,0
Exp/Cntr=0.3,0.1

Type RM Length L Ch R = 1 ,2149    ,183.6,170.6,158.8
XS GIS Cut Line= 2
2219752.15599698464985.4915999032219238.96888043464855.131037257
#Sta/Elev= 30
       0 2490.09    12.4 2489.06    20.6 2490.69    37.1 2490.79    46.3 2489.89
    61.9 2487.03    74.3 2485.91    94.9 2488.01   108.8 2488.22   128.6 2486.68
     145 2489.12   156.8 2489.82   171.4 2488.73   181.6 2486.66   198.1  2487.1
   204.3 2484.95   207.6 2483.87   214.6 2483.35   227.3 2484.72   239.3 2486.35
   255.9 2487.25   268.2 2487.06     293 2489.28   309.5 2486.69   326.1 2485.75
   339.2 2486.87     359    2490   474.6 2493.67   511.7 2496.97   529.5 2499.68
#Mann= 3 ,-1,0
       0      .1       0   204.3    .045       0   227.3      .1       0
#XS Ineff= 2 , 0
          159.89 2491.67  294.76         2490.82
Permanent Ineff=
       F       F
Bank Sta=204.3,227.3
XS Rating Curve= 0 ,0
Exp/Cntr(USF)=0,0
Exp/Cntr=0.3,0.1

Type RM Length L Ch R = 1 ,1978    ,64,98.3,93
XS GIS Cut Line= 4
2219691.43731769464785.6505453582219507.61417579464771.162021858
2219436.07709101464811.910994201 2219256.7816127464780.217349046
#Sta/Elev= 30
       0 2482.64    51.4 2481.73    79.5 2476.85    83.5 2477.06    95.6 2480.05
   103.2 2481.33   119.6 2482.33   135.7 2481.53   147.7 2479.75   159.8 2480.12
   170.8 2481.43   179.8 2481.26     193 2481.87   197.2 2481.39   209.6 2478.19
   226.5 2477.31   229.8 2477.44   232.4 2478.12   238.3 2479.65     250 2480.59
   266.6 2483.15   278.8 2486.58   282.9 2487.31   315.4 2488.58   344.9 2488.64
   372.2 2489.93   384.4 2489.83   426.1 2496.94   437.2 2499.68   448.8 2503.55
#Mann= 3 ,-1,0
       0      .1       0   209.6    .045       0   232.4      .1       0
#XS Ineff= 2 , 0
          189.58 2484.66
Permanent Ineff=
       F       F
Bank Sta=209.6,232.4
XS Rating Curve= 0 ,0
Exp/Cntr(USF)=0,0
Exp/Cntr=0.3,0.1

Type RM Length L Ch R = 1 ,1880    ,111.7,175.4,112.6
XS GIS Cut Line= 5
2219700.06664421464731.9957665692219485.07216903464734.617650412
2219427.39072446 464711.676166782219371.02022182464730.029353686
2219268.11128096464717.575405428
#Sta/Elev= 30
       0 2479.46    19.9 2479.63    39.9 2480.76    59.9 2480.45    71.9  2479.8
    75.9 2479.11    83.7 2475.94    87.9 2474.93    95.9  2475.9   107.9 2479.25
   120.2 2479.98   131.9 2479.79   139.9 2478.29   147.9 2477.77   175.9 2479.06
   195.9 2480.61   241.8 2478.57   250.7 2476.28     263 2476.04   272.2 2476.91
   279.8 2476.55   297.3 2476.53   309.9 2477.74   312.6 2478.56   322.5 2484.55
   343.3 2485.59   367.4 2487.56   391.6 2492.31   418.8 2498.35     440 2504.32
#Mann= 3 ,0,0
       0      .1       0   279.8    .045       0   297.3      .1       0
#XS Ineff= 2 , 0
          194.37 2485.74
Permanent Ineff=
       F       F
Bank Sta=279.8,297.3
XS Rating Curve= 0 ,0
Exp/Cntr(USF)=0,0
Exp/Cntr=0.3,0.1

Type RM Length L Ch R = 1 ,1705    ,125.9,128.8,130.9
XS GIS Cut Line= 3
2219691.48530483464704.7764570982219417.35882602464588.602573713
2219316.74407949464587.596426248
#Sta/Elev= 30
       0 2478.58    14.4 2478.36    38.8 2478.74    55.7 2478.31    60.1 2477.75
    75.4 2473.96    81.6  2473.5   103.5 2477.34   129.6 2477.09   142.6 2475.91
     160 2473.52   177.4 2473.73   181.7 2473.35   185.3 2470.76188.28632469.237
   193.7 2467.93   199.1 2467.62210.78622469.184   218.9 2470.73     228 2471.53
   238.2 2473.55   251.2 2473.82   277.3 2476.49   281.6 2477.64   290.3 2482.15
   298.9  2485.5   345.9 2494.67   361.7 2498.29   376.3 2502.28   398.3 2509.04
#Mann= 3 ,-1,0
       0      .1       0188.2863    .045       0210.7862      .1       0
Bank Sta=188.2863,210.7862
XS Rating Curve= 0 ,0
Exp/Cntr(USF)=0,0
Exp/Cntr=0.3,0.1

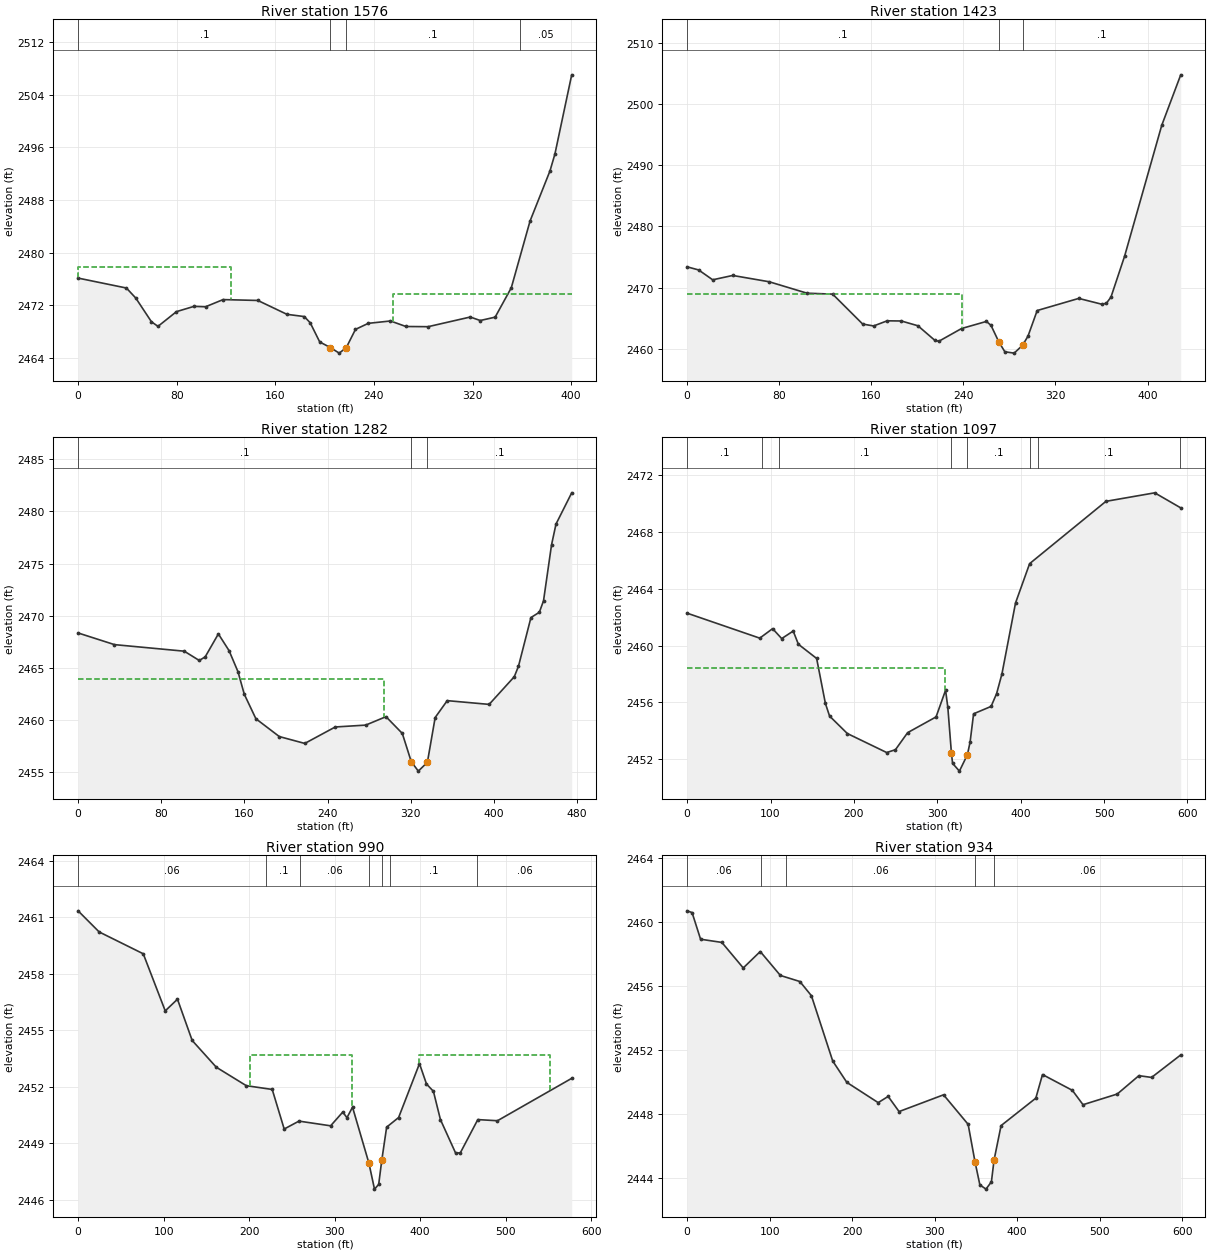
Type RM Length L Ch R = 1 ,1576    ,159.8,152.9,145.4
XS GIS Cut Line= 3
2219747.91405922464627.479087413 2219537.3397136464496.153151436
2219386.76773528 464474.07680875
#Sta/Elev= 30
       0 2476.12    39.2 2474.61    46.8 2473.08    59.5 2469.48    64.8 2468.78
    79.8 2471.02      94 2471.82   103.4 2471.76   117.6 2472.85   145.8 2472.72
   169.4 2470.61   183.5 2470.27   188.3 2469.32     196 2466.41   204.7 2465.55
   211.8 2464.71   217.5 2465.53     225 2468.32   235.4 2469.24   253.4  2469.6
   265.9 2468.76   283.9 2468.73   318.1  2470.2   326.2 2469.67   338.3 2470.18
   351.4 2474.65   366.6 2484.79   382.8 2492.43   386.8    2495   400.4 2507.03
#Mann= 4 ,-1,0
       0      .1       0   204.7    .045       0   217.5      .1       0
  358.17     .05       0
#XS Ineff= 2 , 0
          123.94 2477.85  255.21         2473.65
Permanent Ineff=
       F       F
Bank Sta=204.7,217.5
XS Rating Curve= 0 ,0
Exp/Cntr(USF)=0,0
Exp/Cntr=0.3,0.1

Type RM Length L Ch R = 1 ,1423    ,132.8,141.5,148.1
XS GIS Cut Line= 5
2219808.29902555464546.3082313212219771.33459173464463.462370005
2219643.75900655464377.8465970432219574.31783059464372.280868684
2219459.61701956464367.250131358
#Sta/Elev= 30
       0 2473.39      10 2472.88    22.2 2471.27    39.6 2471.98    71.3 2470.95
   104.2 2469.08   126.4 2468.93   152.5 2464.04     162 2463.73   173.8 2464.57
   186.1 2464.54   200.5 2463.76     215 2461.41   218.6 2461.22   238.4 2463.31
     260 2464.47     264 2463.82270.64952461.175     276 2459.51   284.1 2459.29
291.41412460.575   296.1 2462.06   304.1 2466.25   340.2 2468.23   360.2 2467.28
   364.2 2467.43   368.2 2468.45     380 2475.11   412.3 2496.51   428.8 2504.76
#Mann= 3 ,-1,0
       0      .1       0270.6495    .045       0291.4141      .1       0
#XS Ineff= 2 , 0
          238.87 2468.93
Permanent Ineff=
       F       F
Bank Sta=270.6495,291.4141
XS Rating Curve= 0 ,0
Exp/Cntr(USF)=0,0
Exp/Cntr=0.3,0.1

Type RM Length L Ch R = 1 ,1282    ,189.1,184.4,180.2
XS GIS Cut Line= 4
2219909.71869004 464462.093688482219899.09524869464419.958982635
2219641.00255184464239.1560773572219525.06786449464246.056951604
#Sta/Elev= 30
       0 2468.33      35 2467.21   102.1 2466.58   116.5 2465.69   122.2 2466.03
   134.9 2468.24   145.2 2466.63   153.8  2464.6   159.8 2462.45     171 2460.09
   193.5 2458.38     218 2457.72   247.3  2459.3   276.6 2459.48   296.1 2460.29
   311.8 2458.68   320.4 2455.97   327.2 2455.06  335.92 2455.91   343.4 2460.21
     355 2461.83   395.3 2461.47   419.5 2464.13   423.5 2465.13   435.5 2469.81
   443.6 2470.32   447.6 2471.42   455.3 2476.79   459.6 2478.79   474.7 2481.79
#Mann= 3 ,-1,0
       0      .1       0   320.4    .045       0  335.92      .1       0
#XS Ineff= 2 , 0
          294.65 2463.94
Permanent Ineff=
       F       F
Bank Sta=320.4,335.92
XS Rating Curve= 0 ,0
Exp/Cntr(USF)=0,0
Exp/Cntr=0.3,0.1

Type RM Length L Ch R = 1 ,1097    ,101.4,106.7,111.1
BEGIN DESCRIPTION:
structure xs 4
END DESCRIPTION:
XS GIS Cut Line= 4
2219998.46089648464351.6186967952219801.70715774464119.737854907
2219700.08626375464087.5411360192219526.02275226464137.848509282
#Sta/Elev= 30
       0 2462.29    87.1 2460.53   102.5  2461.2   113.4  2460.5   127.2 2461.03
   133.4  2460.1   155.3  2459.1   165.8 2455.93   170.8 2455.04   192.1 2453.81
   239.3 2452.47   249.8 2452.67   264.4 2453.87   298.5 2454.98   309.9 2456.86
   312.6 2455.66316.94032452.419   318.3 2451.71   326.5 2451.16336.04032452.311
   339.3  2453.2   343.5  2455.2   364.5 2455.72   371.1 2456.62   377.5 2458.01
   393.8 2463.01   410.7 2465.78   502.2 2470.17   560.7 2470.77   591.9 2469.71
#Mann= 8 ,-1,0
       0      .1       0      90     .06       0     110      .1       0
316.9403    .045       0336.0403      .1       0  410.71     .06       0
  420.71      .1       0  590.71     .06       0
#XS Ineff= 2 , 0
          309.63 2458.46
Permanent Ineff=
       F       F
Bank Sta=316.9403,336.0403
XS Rating Curve= 0 ,0
Exp/Cntr(USF)=0,0
Exp/Cntr=0.5,0.3

Type RM Length L Ch R = 1 ,990     ,56.3,56.3,56.7
BEGIN DESCRIPTION:
structure xs 3; 15.2 ft between structure and xs
END DESCRIPTION:
XS GIS Cut Line= 5
2220064.56478495464288.2314064842219865.75062458 464044.69907469
2219824.09611952464013.0054295352219745.31477299463997.611373317
2219619.04268733464029.249048929
#Sta/Elev= 30
       0 2461.33    24.6 2460.21    76.2 2459.05   101.9 2456.02   116.2 2456.64
   133.4 2454.45   161.6 2453.03   196.7 2452.05     227 2451.85     241 2449.75
   258.3 2450.17   295.3 2449.92   309.5 2450.65   314.4 2450.35   320.9 2450.91
340.03372447.945   346.6 2446.56   351.5 2446.81355.13372448.101   360.8 2449.85
   374.8 2450.36   399.2 2453.22   407.4 2452.14   415.5 2451.75   423.7 2450.25
   441.5 2448.47     447 2448.49   467.4 2450.25   490.4 2450.19   577.2 2452.44
#Mann= 7 ,-1,0
       0     .06       0     220      .1       0     260     .06       0
340.0337    .045       0355.1337     .06       0  364.38      .1       0
  466.99     .06       0
#XS Ineff= 5 ,-1
  201.46  320.11 2453.67  320.11     325  2449.8     370  398.87  2448.8
  398.87  552.34 2453.67  552.34   577.2  2448.8
Permanent Ineff=
       F       F       F       F       F
Bank Sta=340.0337,355.1337
XS Rating Curve= 0 ,0
Exp/Cntr(USF)=0,0
Exp/Cntr=0.5,0.3

Type RM Length L Ch R = 1 ,934     ,73.4,69.5,64.9
BEGIN DESCRIPTION:
structure xs 2; 14.5 ft between structure and xs
END DESCRIPTION:
XS GIS Cut Line= 5
2220102.59715913464253.8211631732219887.74381094463990.740020422
2219846.08930588463959.0463752672219767.30795935463943.652319049
2219646.20866889463977.633683962
#Sta/Elev= 30
       0 2460.72       6 2460.61    16.3 2458.94    42.1 2458.74      68 2457.14
    88.6 2458.17     113 2456.67   136.6 2456.29   150.6  2455.4   176.4 2451.31
   193.5 2449.97   231.5  2448.7   243.6 2449.09   256.8 2448.14   310.7 2449.19
   340.5 2447.34348.82022444.992   354.7 2443.55   362.1 2443.28   368.7 2443.74
371.92022445.106   380.4 2447.26   422.5 2448.98   430.6 2450.46   466.8 2449.47
   479.7 2448.57   521.2 2449.24   547.4 2450.39   562.8 2450.28   598.1 2451.69
#Mann= 5 ,-1,0
       0     .06       0      90     .05       0     120     .06       0
348.8202    .045       0371.9202     .06       0
#XS Ineff= 2 , 0
           343.8  2446.1     376          2445.6
Permanent Ineff=
       F       F
Bank Sta=348.8202,371.9202
XS Rating Curve= 0 ,0
Exp/Cntr(USF)=0,0
Exp/Cntr=0.5,0.3

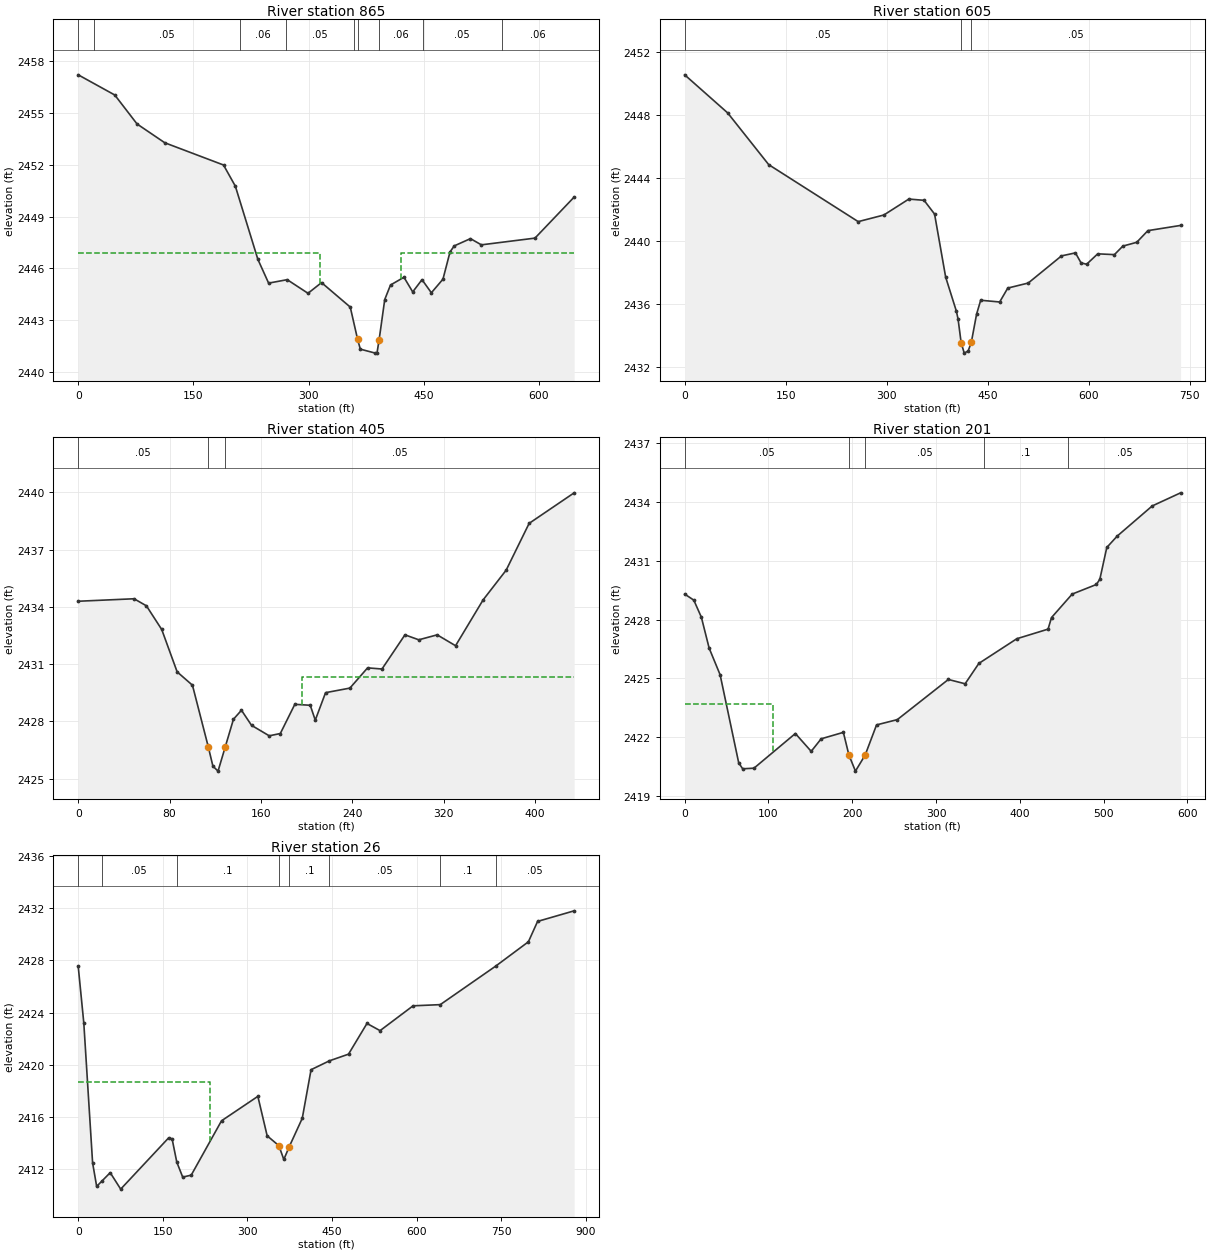
Type RM Length L Ch R = 1 ,865     ,256.9,259.6,263.4
BEGIN DESCRIPTION:
structure xs 1
END DESCRIPTION:
XS GIS Cut Line= 4
2220154.86491804464198.2173571972219942.56780287463934.606721302
2219802.71330521463873.2317259212219655.81577528463921.023730521
#Sta/Elev= 30
       0 2457.22    47.6 2456.05    76.6 2454.37   112.7 2453.28   189.2 2451.99
   204.6 2450.76   233.9 2446.52   247.9 2445.14   272.1 2445.34   299.2 2444.55
   316.8 2445.17   354.2 2443.75   363.7 2441.89   367.3 2441.31   386.9 2441.08
   389.1 2441.11   391.8 2441.86   399.1 2444.19   406.6 2445.03   424.1 2445.48
   435.5 2444.63   447.6 2445.34   459.8 2444.58   474.9 2445.37   484.1 2446.95
   489.6  2447.3   510.7 2447.72   524.9 2447.36   594.7 2447.75   645.7 2450.13
#Mann= 9 ,-1,0
       0     .06       0      20     .05       0     210     .06       0
     270     .05       0  358.47     .06       0   363.7    .045       0
   391.8     .06       0  448.47     .05       0   551.2     .06       0
#XS Ineff= 2 , 0
           314.7 2446.86  420.39         2446.86
Permanent Ineff=
       F       F
Bank Sta=363.7,391.8
XS Rating Curve= 0 ,0
Exp/Cntr(USF)=0,0
Exp/Cntr=0.3,0.1

Type RM Length L Ch R = 1 ,605     ,199.3,199.6,197.6
XS GIS Cut Line= 4
2220263.62945903 464055.948105612220217.34667563463802.398944368
2220010.08029779463685.6858383992219777.15715959463747.262063273
#Sta/Elev= 30
       0 2450.54    63.8 2448.13   124.8 2444.85   257.7 2441.24   295.8 2441.66
   332.9 2442.67   355.5 2442.59   371.1 2441.72   387.6 2437.72   403.4 2435.58
     406 2435.07   410.6 2433.56   415.2 2432.91     421 2433.05   425.7  2433.6
   433.5 2435.38   439.6 2436.26   467.8 2436.15   479.8 2437.03   510.2 2437.35
   559.6 2439.07   580.3 2439.26   588.6 2438.63   596.9 2438.54   613.4  2439.2
   638.2 2439.15   650.7 2439.69   671.3 2439.93   687.9 2440.67   736.5    2441
#Mann= 3 ,-1,0
       0     .05       0   410.6    .045       0   425.7     .05       0
Bank Sta=410.6,425.7
XS Rating Curve= 0 ,0
Exp/Cntr(USF)=0,0
Exp/Cntr=0.3,0.1

Type RM Length L Ch R = 1 ,405     ,197.8,204,212.6
XS GIS Cut Line= 3
2220249.44277978463601.571910304 2220046.2009918463498.944868849
2219840.94690889463521.080113085
#Sta/Elev= 30
       0 2434.29    48.9 2434.42    59.7 2434.05    73.1 2432.81    86.6 2430.59
     100 2429.89  113.82 2426.67   117.9 2425.65   122.4 2425.39   128.7 2426.66
   135.9 2428.11   142.9 2428.58   151.7 2427.79   167.2 2427.24   176.9 2427.36
   189.6 2428.89   203.1 2428.84   207.5 2428.06   216.5  2429.5   237.8 2429.74
   253.3  2430.8   265.9 2430.74     286 2432.53   298.1 2432.27   314.2 2432.53
   330.3 2431.96   354.4 2434.36   374.6 2435.92   394.7 2438.37   434.1 2439.97
#Mann= 3 ,-1,0
       0     .05       0  113.82    .045       0   128.7     .05       0
#XS Ineff= 2 , 0
                          195.77         2430.31
Permanent Ineff=
       F       F
Bank Sta=113.82,128.7
XS Rating Curve= 0 ,0
Exp/Cntr(USF)=0,0
Exp/Cntr=0.3,0.1

Type RM Length L Ch R = 1 ,201     ,188.4,175.8,188.4
XS GIS Cut Line= 5
2220353.42972222463562.8996987852220271.93177753463402.620407571
2220245.14578477463360.6506027792220137.31715802463366.675458353
2219890.70250295463428.880856414
#Sta/Elev= 30
       0 2429.31    10.9    2429    19.9 2428.13    29.2 2426.55    42.3 2425.19
    64.5 2420.69    69.2 2420.39    82.7 2420.42   132.1 2422.19     151 2421.28
   162.9 2421.92   189.4 2422.25195.96832421.098   203.8 2420.27   215.4 2421.09
     229 2422.63   253.8  2422.9   314.7 2424.95   334.7 2424.73   351.1 2425.77
   396.4 2427.03   433.7 2427.52   437.8 2428.11   462.5 2429.31   491.4  2429.8
   495.5 2430.07   503.8 2431.69   516.2 2432.27     558 2433.81   591.9 2434.48
#Mann= 5 ,-1,0
       0     .05       0195.9683    .045       0   215.4     .05       0
   357.6      .1       0   457.6     .05       0
#XS Ineff= 2 , 0
          105.65 2423.69
Permanent Ineff=
       F       F
Bank Sta=195.9683,215.4
XS Rating Curve= 0 ,0
Exp/Cntr(USF)=0,0
Exp/Cntr=0.3,0.1

Type RM Length L Ch R = 1 ,26      ,,,
XS GIS Cut Line= 4
2220703.75014014 463507.626537682220469.95303806 463313.09792964
2220356.99688672463283.0251880512219908.78664326463377.036784747
#Sta/Elev= 30
       0 2427.54     9.9 2423.21    25.5  2412.5    32.7  2410.7    41.4 2411.08
    56.7 2411.75    75.3 2410.49   160.2 2414.41   166.4 2414.34   174.7 2412.56
   185.2 2411.41   200.3 2411.56     254 2415.72   318.4 2417.59   334.9 2414.57
  355.652413.816   364.4 2412.76  374.152413.747   397.1 2415.91   412.7 2419.63
   445.2 2420.31   479.1 2420.82   511.8 2423.17     535 2422.62   593.5 2424.52
   641.7 2424.61     740 2427.56   797.9 2429.42   814.2 2430.98     879 2431.79
#Mann= 8 ,-1,0
       0      .1       0    41.4     .05       0   174.7      .1       0
  355.65    .045       0  374.15      .1       0   445.2     .05       0
   641.7      .1       0     740     .05       0
#XS Ineff= 2 , 0
          234.22 2418.66
Permanent Ineff=
       F       F
Bank Sta=355.65,374.15
XS Rating Curve= 0 ,0
Exp/Cntr(USF)=0,0
Exp/Cntr=0.3,0.1
LCMann Table=0

Chan Stop Cuts=-1
Use User Specified Reach Order=0
Composite Channel Slope=5